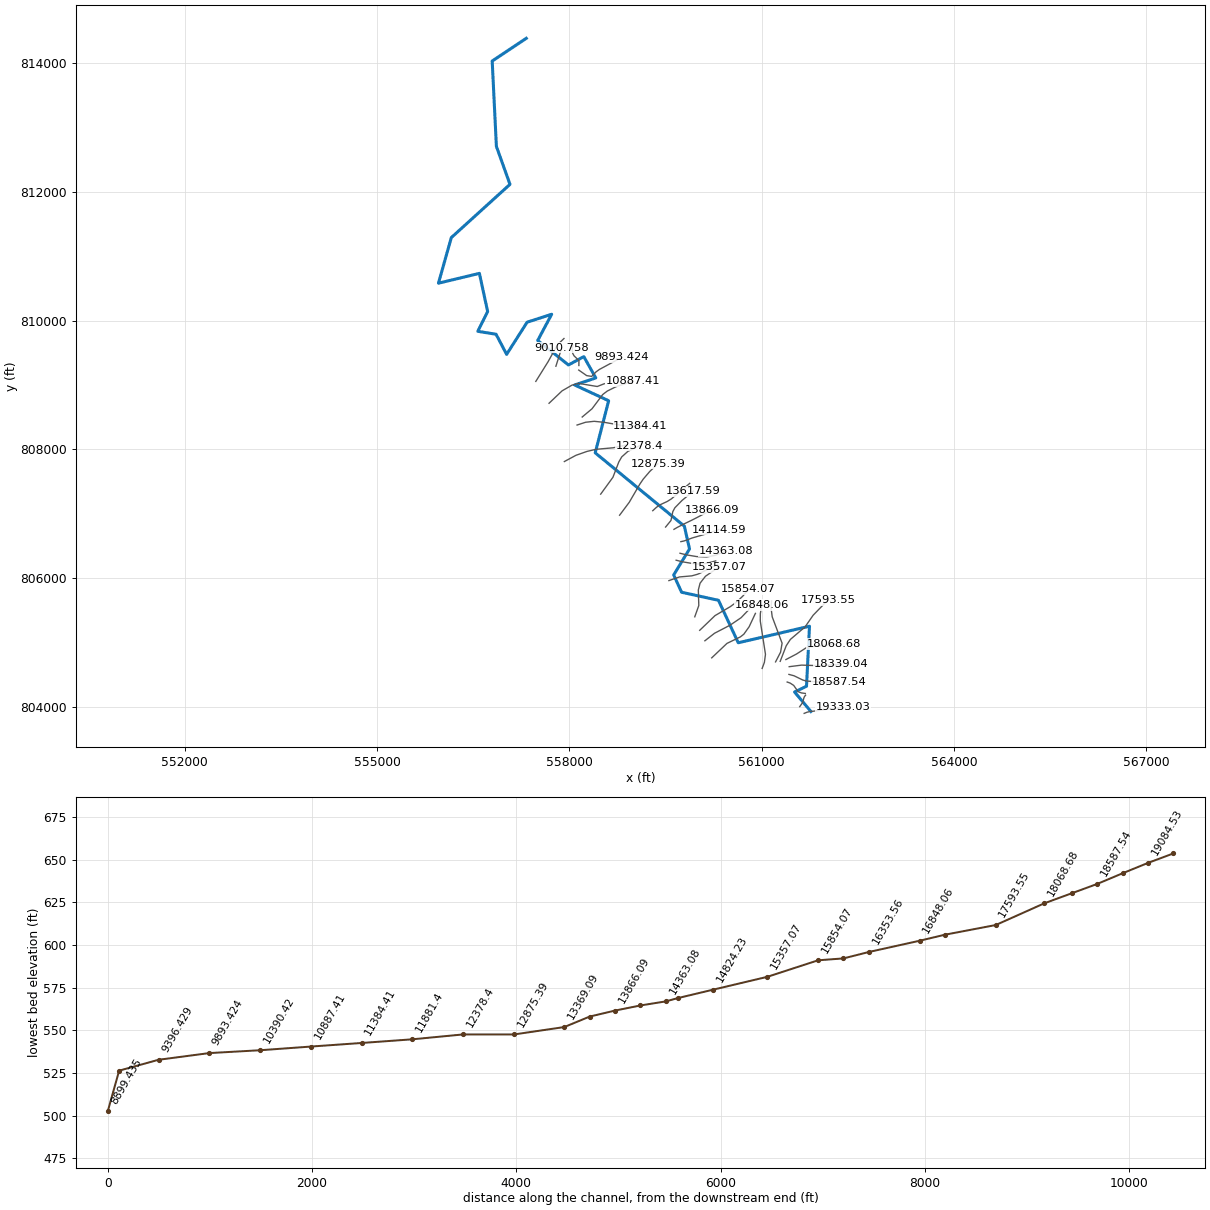
--- 11038_ras.prj (project) ---

Proj Title=11038
Current Plan=p01
Default Exp/Contr=0.3,0.1
English Units
Geom File=g01
Flow File=f01
Plan File=p01
Y Axis Title=Elevation
X Axis Title(PF)=Main Channel Distance
X Axis Title(XS)=Station
BEGIN DESCRIPTION:
RFD model 11038 exported to HEC-RAS
END DESCRIPTION:

--- 11038_ras.p01 (plan) ---

Plan Title=Plan 01
Program Version=4.10
Short Identifier=Plan 01
Geom File=g01
Flow File=f01
Subcritical Flow
Calc Critical at every XS
Secant Critical Depth

--- 11038_ras.f01 (steady flow) ---

Flow Title=Flow 01
Program Version=5.01
Number of Profiles= 6
Profile Names=10yr,25yr,50yr,100yr,100plus,500yr
River Rch & RM=11038,50,19333.03
  286.09  459.56  622.26  771.13 1125.85 1821.52
River Rch & RM=11038,50,19084.53
  287.87  462.44  626.19  776.01 1132.98 1831.49
River Rch & RM=11038,50,18836.03
  294.96  473.92  641.82  795.46 1161.37 1871.17
River Rch & RM=11038,50,18587.54
   298.5  479.64  649.62  805.16 1175.53 1890.89
River Rch & RM=11038,50,18339.04
  303.79  488.21  661.28  819.66  1196.7 1920.31
River Rch & RM=11038,50,18068.68
  308.36   495.6  671.35  832.18 1214.99 1945.67
River Rch & RM=11038,50,17593.55
 1027.93 1663.89 2266.84  2819.3 4116.18 5581.81
River Rch & RM=11038,50,17096.55
 1054.02 1706.41 2325.09 2891.98 4222.29 5706.03
River Rch & RM=11038,50,16848.06
 1060.45 1716.89 2339.45 2909.89 4248.45  5736.6
River Rch & RM=11038,50,16353.56
 1179.75 1911.33 2605.78 3242.21 4733.63  6298.6
River Rch & RM=11038,50,16102.56
 1185.76 1921.13 2619.22 3258.99 4758.12 6326.78
River Rch & RM=11038,50,15854.07
 1192.03 1931.36 2633.23 3276.49 4783.67 6356.14
River Rch & RM=11038,50,15357.07
 1196.73 1939.03 2643.74  3289.6 4802.81 6378.13
River Rch & RM=11038,50,14824.23
 1355.55 2198.35 2999.42 3733.85 5451.42 7117.21
River Rch & RM=11038,50,14480.89
 1389.48 2253.74 3075.38 3828.69 5589.89  7273.2
River Rch & RM=11038,50,14363.08
 1390.23 2254.98 3077.07 3830.81 5592.98 7276.67
River Rch & RM=11038,50,14114.59
 1391.75 2257.45 3080.46 3835.04 5599.16 7283.63
River Rch & RM=11038,50,13866.09
 1589.38 2580.22 3523.31 4388.18 6406.74 8183.36
River Rch & RM=11038,50,13617.59
 1591.56 2583.81 3528.24 4394.34 6415.74 8193.32
River Rch & RM=11038,50,13369.09
 1595.95 2590.98 3538.09 4406.66 6433.72 8213.22
River Rch & RM=11038,50,12875.39
 1665.69 2705.04 3694.72 4602.44 6719.56 8528.05
River Rch & RM=11038,50, 12378.4
 1701.99 2764.47  3776.4  4704.6 6868.72 8691.86
River Rch & RM=11038,50, 11881.4
 1716.58 2788.38 3809.27 4745.72 6928.75  8757.7
River Rch & RM=11038,50,11384.41
  1841.2 2992.41 4089.68 5096.44  7440.8 9315.49
River Rch & RM=11038,50,10887.41
 1937.98 3151.18  4308.2 5370.05 7840.27 9748.08
River Rch & RM=11038,50,10390.42
 1944.46 3161.82 4322.84 5388.39 7867.05    9777
River Rch & RM=11038,50,9893.424
 1949.77 3170.54 4334.85 5403.44 7889.02 9800.72
River Rch & RM=11038,50,9396.429
 1956.22 3181.14 4349.46 5421.74 7915.74 9829.58
River Rch & RM=11038,50,9010.758
 1959.68 3186.82 4357.28 5431.54 7930.06 9845.02
River Rch & RM=11038,50,8899.435
 1961.52 3189.85 4361.45 5436.77 7937.69 9853.25
River Rch & RM=11038,50, 8402.44
 1965.89 3197.02 4371.34 5449.17 7955.78 9872.79
River Rch & RM=11038,50,7905.446
 2015.08 3277.91 4482.84 5588.96 8159.8810092.87
River Rch & RM=11038,50,7408.451
 2029.88 3302.27 4516.42 5631.06 8221.3610159.04
River Rch & RM=11038,50,6804.901
  2087.7  3397.2 4647.15 5794.83 8460.4510414.98
River Rch & RM=11038,50,6414.462
 2098.61 3415.12 4671.84 5825.77 8505.6210463.26
River Rch & RM=11038,50,5917.468
 2112.43 3437.84 4703.15 5865.01 8562.9210524.49
River Rch & RM=11038,50, 5668.97
 2115.59 3443.04 4710.32    5874 8576.0510538.52
River Rch & RM=11038,50,5392.999
 2122.14 3453.81 4725.16 5892.62 8603.2210567.57
River Rch & RM=11038,50,4674.981
 2127.56 3462.72 4737.45 5908.02 8625.7110591.58
River Rch & RM=11038,50,4177.987
 2134.79  3474.6 4753.82 5928.55 8655.6810623.56
River Rch & RM=11038,50, 3929.49
 2135.46 3475.71 4755.36 5930.47 8658.4910626.56
Boundary for River Rch & Prof#=11038,50,1
Up Type= 0
Dn Type= 2
Boundary for River Rch & Prof#=11038,50,2
Up Type= 0
Dn Type= 2
Boundary for River Rch & Prof#=11038,50,2
Up Type= 0
Dn Type= 2
Boundary for River Rch & Prof#=11038,50,2
Up Type= 0
Dn Type= 2
Boundary for River Rch & Prof#=11038,50,2
Up Type= 0
Dn Type= 2
Boundary for River Rch & Prof#=11038,50,2
Up Type= 0
Dn Type= 2

--- 11038_ras.g01 (geometry) ---

Geom Title=11038
Program Version=4.10

River Reach=11038,50
Reach XY= 30
561767.649474382803929.835269168561512.788363308804232.613046974
561698.899474382804322.196380302561745.438141763805254.008792415
560634.220727414804997.137025177560325.726063579805656.754058272
559750.515696466805781.650809988559627.480249256 806050.42397593
559874.276599407806454.233266145559793.904240966806807.754280284
558403.578489095 807946.70480831558613.110119909808755.598727897
558082.808321416808999.967388272 558412.40137881809109.897973955
558225.680735111809440.568980858 557985.63726601809311.156480849
557506.711723834809691.492390603557724.616793096 810098.49623315
557341.459345728809974.998393223557022.020774305809475.690775588
556857.170105398809787.830668941556572.719131172809833.481169298
556726.039788097 810140.77962783556597.285349399810733.323754385
 555958.56943202810580.869295135556159.566294134811289.194985405
557074.286465734812115.718588859556862.227104813 812705.79881613
556796.888742775814030.673941299557328.051981121814383.212157667

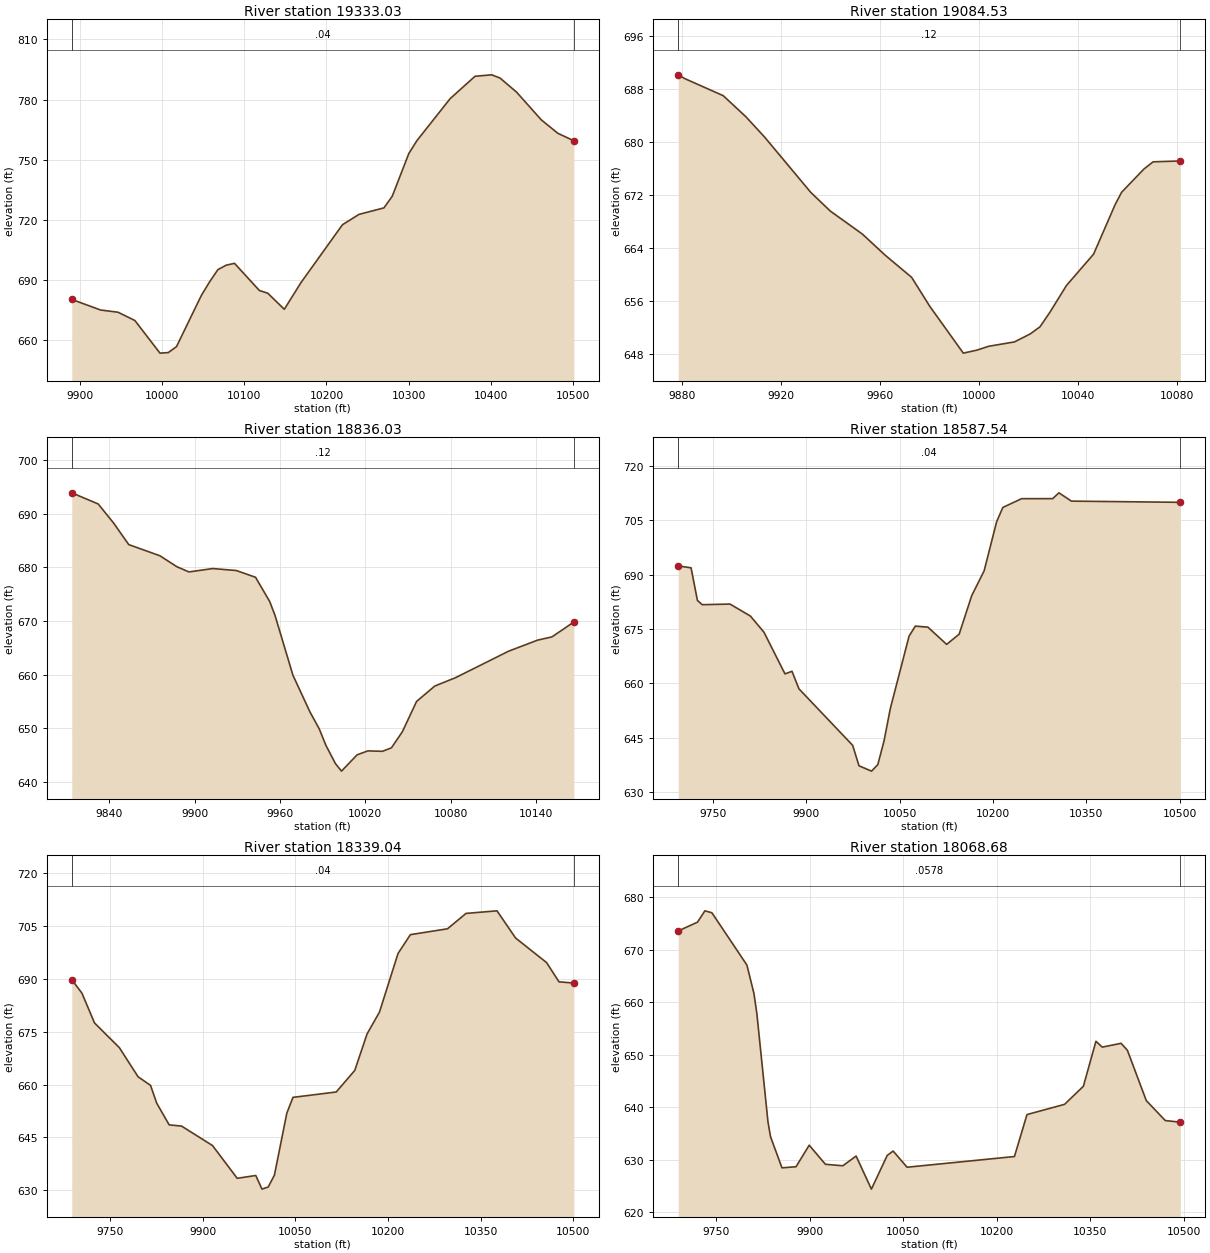
Type RM Length L Ch R = 1 ,19333.03,248.497200,248.497200,248.497200
XS GIS Cut Line= 6
561662.418468546 803900.73475208561708.538646921803919.102840223
561752.457522983803929.269625189561812.871842973803935.498401967
562040.147122079803967.956850907562264.268180975803996.040851384
#Sta/Elev= 30
9890.075680.42649925.145675.1547 9946.35674.04459966.879669.9166 9997.41653.6695
10007.46653.937510017.51656.896210047.68682.342210057.79689.189610067.89695.2726
10077.99 697.47710088.09 698.40410118.39684.8595 10128.5683.5392 10148.7675.5141
 10168.9688.758510219.41717.629510239.61722.804210269.92726.029810280.01731.8118
10300.16753.087410310.24759.649210350.55  780.4910380.79791.609310400.94792.3219
10411.02790.760310431.18783.754910461.41769.880310481.57 763.17710500.99759.4694
#Mann= 3 , 0 , 0
9890.075    0.04       09890.075    0.04       010500.99    0.04       0
#XS Ineff= 2 , 0
       0                               0
Bank Sta=9890.075,10500.99
Exp/Cntr=0.3,0.1

Type RM Length L Ch R = 1 ,19084.53,248.497300,248.497300,248.497300
XS GIS Cut Line= 6
561593.146023523804005.468091597561632.318260771804059.908914762
561644.625443325804090.328954276561657.095337329804139.009561247
561667.776500435804162.955584708561684.355835691804183.340785073
#Sta/Elev= 26
9878.338690.17189881.182 689.5669896.523687.01879905.646683.8454 9913.22680.7709
9931.904672.39939939.766669.58639952.728666.10829961.857662.94129972.644 659.563
9979.928655.20749993.521648.1088    9999648.557910003.81649.145210014.16649.8011
10020.52 651.00110024.51 652.08510028.66 654.37210035.21658.337910046.16663.0692
10054.88670.565510057.48672.421410066.54675.946910070.22677.024410079.82 677.136
 10081.2677.2141
#Mann= 3 , 0 , 0
9878.338    0.12       09878.338    0.12       0 10081.2    0.12       0
#XS Ineff= 2 , 0
       0                               0
Bank Sta=9878.338,10081.2
Exp/Cntr=0.3,0.1

Type RM Length L Ch R = 1 ,18836.03,248.497300,248.497300,248.497300
XS GIS Cut Line= 6
561397.179628886804387.723340407561444.700197116804370.599524505
561498.941858791804334.924848111561568.081099884 804237.82429657
561620.309178159804218.018146162561680.367169488804210.138341726
#Sta/Elev= 30
 9813.52693.89599832.088691.82339842.773688.32879853.602 684.2519875.513682.1702
9887.407 680.1399895.883  679.169912.648679.78739929.191679.42389942.779678.1622
9952.702673.65779956.471671.06199969.052659.92679980.959653.12069987.548649.9326
9992.342646.8088    9999643.433110003.23642.049710014.18645.085610021.77 645.823
10031.98645.738710038.35646.393410046.02649.384810056.04655.035110068.84657.9013
10083.35659.451210120.84664.402810141.09666.448510151.22667.057910166.63669.8262
#Mann= 3 , 0 , 0
 9813.52    0.12       0 9813.52    0.12       010166.63    0.12       0
#XS Ineff= 2 , 0
       0                               0
Bank Sta=9813.52,10166.63
Exp/Cntr=0.3,0.1

Type RM Length L Ch R = 1 ,18587.54,248.497200,248.497200,248.497200
XS GIS Cut Line= 6
561424.794574425804505.714471349561504.575735773804484.522197187
 561639.58772434804419.237497451561690.276363808804404.654258138
561946.844976215804380.707013808562209.895800039804383.451468143
#Sta/Elev= 30
 9694.53692.38519715.136 691.8529725.335  682.879733.071 681.6879777.679681.8567
9810.439678.54839832.331674.07299865.992662.60399877.212663.32559888.432658.4848
9974.697642.90419984.858637.2561   10005635.789410015.06637.567210025.11644.1311
10035.16653.035110065.32673.024610075.38675.772310095.48675.502910125.64670.7416
10145.75673.5549 10165.8684.122310185.85691.0115 10205.9 704.54310215.92708.4989
10245.98710.915610295.98710.928810305.99712.531410325.99710.243210500.96709.9104
#Mann= 3 , 0 , 0
 9694.53    0.04       0 9694.53    0.04       010500.96    0.04       0
#XS Ineff= 2 , 0
       0                               0
Bank Sta=9694.53,10500.96
Exp/Cntr=0.3,0.1

Type RM Length L Ch R = 1 ,18339.04,270.359800,270.359800,270.359800
XS GIS Cut Line= 6
561428.880011466804625.658455698561622.437498683804650.178217376
561791.333138781804644.698331585561924.465586707804645.359571066
562090.722212696804653.291896354562238.965419523 804665.75057018
#Sta/Elev= 30
 9688.14689.72689704.573685.90879724.962677.45929765.289 670.4239795.522662.1931
9815.677659.75189825.755654.67799845.837648.56159865.901648.21289915.972642.7028
9955.989633.40959986.049 634.2099996.102630.344110006.17630.951710016.23634.3162
10036.26 651.85910046.27 656.35910116.28 657.88310146.28663.992610166.28674.3686
10186.28 680.52710216.32697.145510236.34702.484810296.41704.147710326.44708.5091
10376.56709.241810406.66701.538110456.84694.567110476.91689.119210500.96688.7609
#Mann= 3 , 0 , 0
 9688.14    0.04       0 9688.14    0.04       010500.96    0.04       0
#XS Ineff= 2 , 0
       0                               0
Bank Sta=9688.14,10500.96
Exp/Cntr=0.3,0.1

Type RM Length L Ch R = 1 ,18068.68,475.132000,475.132000,475.132000
XS GIS Cut Line= 6
 561377.57218858804736.244174528561544.205913331804823.291122401
561692.862984836804918.625574474561754.023314521804933.177393929
561977.261792484804955.829089748562128.827018822804978.397714059
#Sta/Elev= 30
9688.698673.56369719.722675.25439731.442677.40159742.686677.03629798.905667.0744
9810.149661.66199814.834657.85239832.636637.27049836.708634.42249855.124628.4707
9877.654628.67769898.851632.7819 9924.79629.14759952.753628.8619 9974.08630.7139
9998.623624.4169   10024630.836210033.47631.672310055.83628.585110228.12630.6236
10248.22 638.61210308.53640.558710338.68 643.99710358.85 652.56610368.94651.4523
10399.21652.1776 10409.3650.855510439.67641.266310470.07637.473510494.21637.1594
#Mann= 3 , 0 , 0
9688.698  0.0578       09688.698  0.0578       010494.21  0.0578       0
#XS Ineff= 2 , 0
       09928.725                       0
Bank Sta=9688.698,10494.21
Exp/Cntr=0.3,0.1

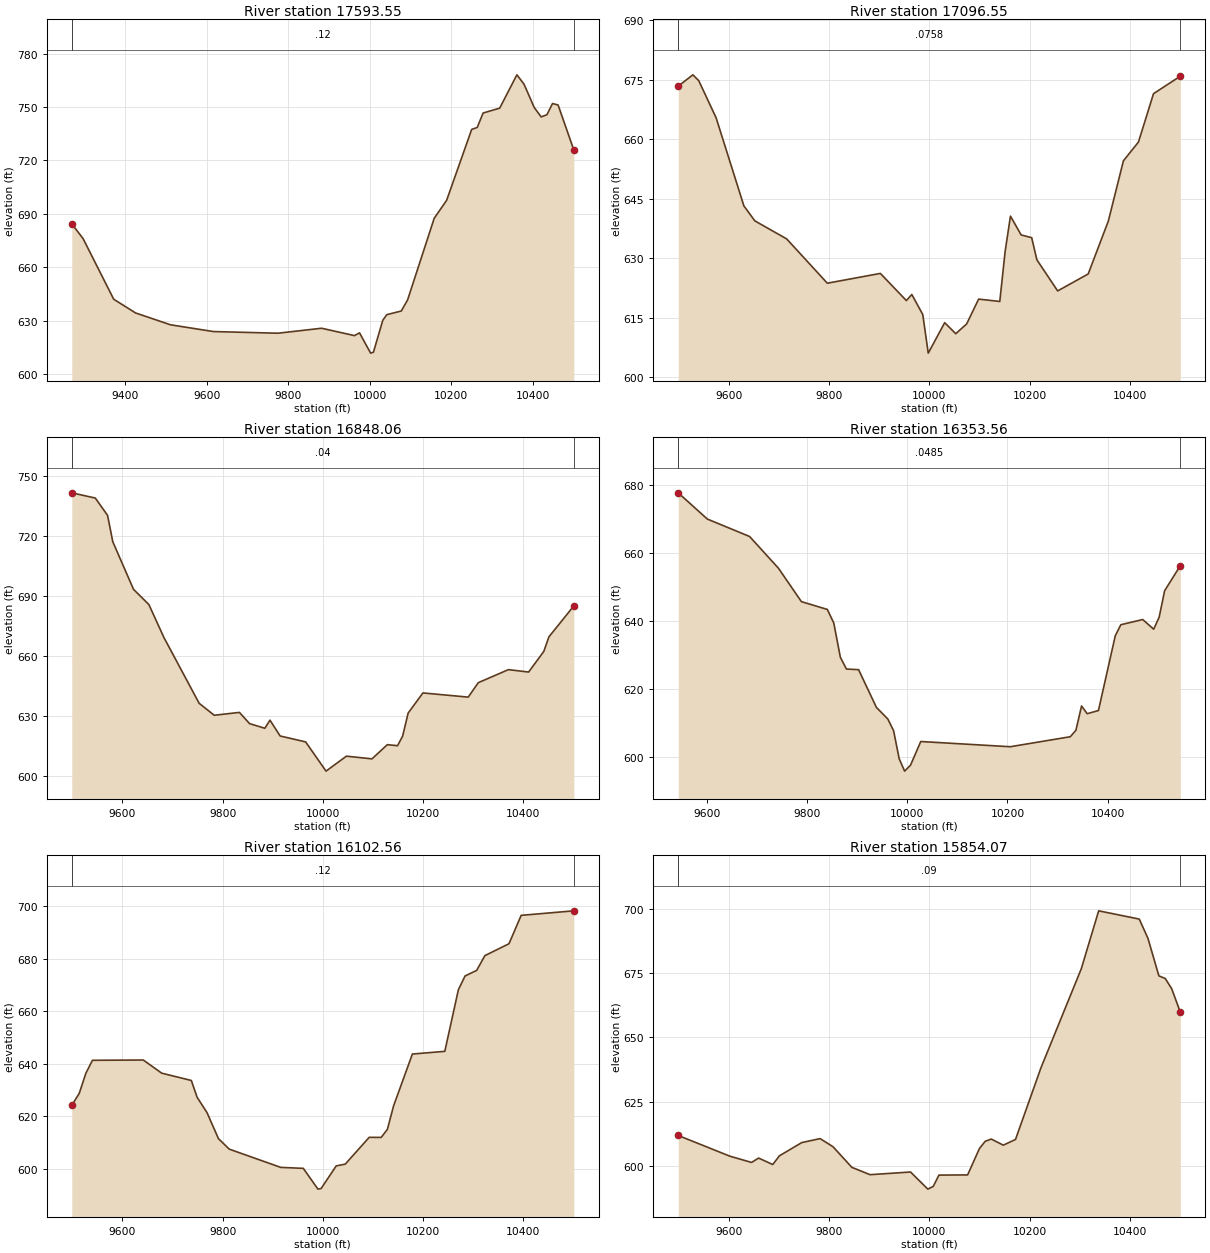
Type RM Length L Ch R = 1 ,17593.55,496.994600,496.994600,496.994600
XS GIS Cut Line= 6
561288.639267147804709.037363946561382.481969893804950.594929531
561446.810577184805048.607700124561677.381747991805244.838635936
561801.989525139805424.496666536562033.203097612805662.109025002
#Sta/Elev= 30
 9268.74 684.3799296.593 676.019 9371.69 641.979 9425.33634.27199511.155627.6118
9616.289 623.8159774.831622.87979881.879625.67549962.537621.53699975.004623.0795
10002.18611.692110009.11612.217310032.12630.180710041.95633.310810077.48635.3637
10092.95641.584210158.24687.447810188.82697.599510250.23737.3968 10263.8 738.499
10278.33746.625910318.97 749.35410361.15768.081310378.56 762.88610403.77749.7153
 10420.8744.439110434.86745.661710448.58751.938210462.29751.147510500.96725.8096
#Mann= 3 , 0 , 0
 9268.74    0.12       0 9268.74    0.12       010500.96    0.12       0
#XS Ineff= 2 , 0
       09882.345                       0
Bank Sta=9268.74,10500.96
Exp/Cntr=0.3,0.1

Type RM Length L Ch R = 1 ,17096.55,248.497200,248.497200,248.497200
XS GIS Cut Line= 6
561216.103179218804700.119227753561294.298006082 804850.79380975
561317.984588118  804991.2438315561163.884456259805400.192543349
561146.656267713805534.153870554561153.258014093805648.207971345
#Sta/Elev= 30
9499.184673.34929528.367676.20959540.096674.74249574.736665.38039630.184643.1573
9652.012639.37929715.513634.83439796.614623.65819902.426626.12799954.304619.2821
9965.227620.81549987.074615.74949997.997606.0252 10030.8613.701210052.81610.9207
10074.58613.381310098.53619.6488 10140.7619.054910151.36631.643510162.01 640.574
10183.32635.832910204.35635.142210214.73629.557110256.17621.7142 10317.1625.9904
10357.31639.349210387.38654.5286 10417.4659.261810447.41671.461310500.87675.8588
#Mann= 3 , 0 , 0
9499.184  0.0758       09499.184  0.0758       010500.87  0.0758       0
#XS Ineff= 2 , 0
       09900.775                       0
Bank Sta=9499.184,10500.87
Exp/Cntr=0.3,0.1

Type RM Length L Ch R = 1 ,16848.06,494.496300,494.496300,494.496300
XS GIS Cut Line= 6
561006.938175979804598.718685234561042.043562748804693.074785707
561058.760957037804818.186611915560977.883752522805333.650047108
560978.907583712805448.559841389561001.108029165805583.749175173
#Sta/Elev= 30
9499.098 741.6779546.049739.06699570.526730.39739580.985717.18969622.368693.3927
9652.904685.82199683.124669.24389753.226636.42889783.303630.42529833.658631.8504
9853.887626.2377  9884.4623.91929894.571627.97159914.912620.05659965.767617.1048
10006.44602.4818 10047.1609.966710098.12608.617110128.73615.722910149.13615.1961
10159.34620.034310170.28631.519910199.79641.585810290.19639.497310310.21646.7191
10370.32653.239910410.66652.039310440.96662.349110451.16669.630110500.91685.1381
#Mann= 3 , 0 , 0
9499.098    0.04       09499.098    0.04       010500.91    0.04       0
#XS Ineff= 2 , 0
       09860.585                       0
Bank Sta=9499.098,10500.91
Exp/Cntr=0.3,0.1

Type RM Length L Ch R = 1 ,16353.56,250.995500,250.995500,250.995500
XS GIS Cut Line= 6
560220.575937002804762.866716456560458.324294688804987.538135456
560667.568554747805088.541299614560721.018476125805129.945264272
560804.353031961805246.200444806560901.925253185805453.657406037
#Sta/Elev= 30
 9543.16677.80079601.178670.08789685.501664.95829743.121655.62099788.929645.7905
9840.717643.4876 9853.56639.47519866.627629.4282 9878.78625.95389903.072625.7688
9938.517614.68469961.455611.23759972.924607.78739983.964599.59689994.814595.9209
10006.59597.654510027.05604.632510205.61603.099910325.45606.044510336.68607.9513
 10347.9615.088210359.12612.813510381.57613.746410415.23635.770710426.28638.9941
10469.96640.5203 10491.8637.684710502.72641.203810513.64648.989610544.93656.3713
#Mann= 3 , 0 , 0
 9543.16  0.0485       0 9543.16  0.0485       010544.93  0.0485       0
#XS Ineff= 2 , 0
       0                10194.26       0
Bank Sta=9543.16,10544.93
Exp/Cntr=0.3,0.1

Type RM Length L Ch R = 1 ,16102.56,248.497300,248.497300,248.497300
XS GIS Cut Line= 6
560113.780937677805027.918386517560264.415574214805145.081353502
560505.934296856805269.881248905560678.498846078 805386.11973805
560789.600026581805501.435012276560879.865294239805645.460237873
#Sta/Elev= 30
9499.063624.09379513.932  628.639527.186636.32889540.329641.28079641.768641.3888
9678.524636.3766 9737.68633.58179749.073 627.2179769.007621.2996 9791.78611.3916
9813.236607.39559915.985600.42859961.109600.05219990.301 592.1329996.629592.3734
10026.73600.982710044.84601.678310092.57611.884110116.55611.8639 10128.9614.9533
10141.25623.901610178.75643.666210243.44644.694810270.52668.184110283.85 673.446
10307.07675.578810323.36681.204410371.57685.757710395.83 696.57710500.93 698.302
#Mann= 3 , 0 , 0
9499.063    0.12       09499.063    0.12       010500.93    0.12       0
#XS Ineff= 2 , 0
       0                               0
Bank Sta=9499.063,10500.93
Exp/Cntr=0.3,0.1

Type RM Length L Ch R = 1 ,15854.07,496.994500,496.994500,496.994500
XS GIS Cut Line= 6
560033.280881885805190.655658511 560272.11280533805418.839127491
 560510.50766128805558.115304958560607.770770262805628.610919546
560707.278599827805723.453144077560795.463775295805828.391704282
#Sta/Elev= 30
9499.047611.88429602.035603.83039645.417601.39999659.468603.0985 9687.57600.5893
9701.083603.98689745.621 609.1259782.227610.6631 9807.83607.51929845.497599.4918
 9881.79596.63559962.598597.67479997.183591.017510007.94592.081810019.23596.4712
10076.51596.540310099.95606.745410111.53 609.60610123.62610.4894 10147.8608.1186
10172.05610.328410222.78638.159710303.32676.707210338.04699.2481   10419 696.039
10436.36688.559410458.17673.950310470.98672.904310483.78668.938910500.93659.8124
#Mann= 3 , 0 , 0
9499.047    0.09       09499.047    0.09       010500.93    0.09       0
#XS Ineff= 2 , 0
       09780.076                       0
Bank Sta=9499.047,10500.93
Exp/Cntr=0.3,0.1

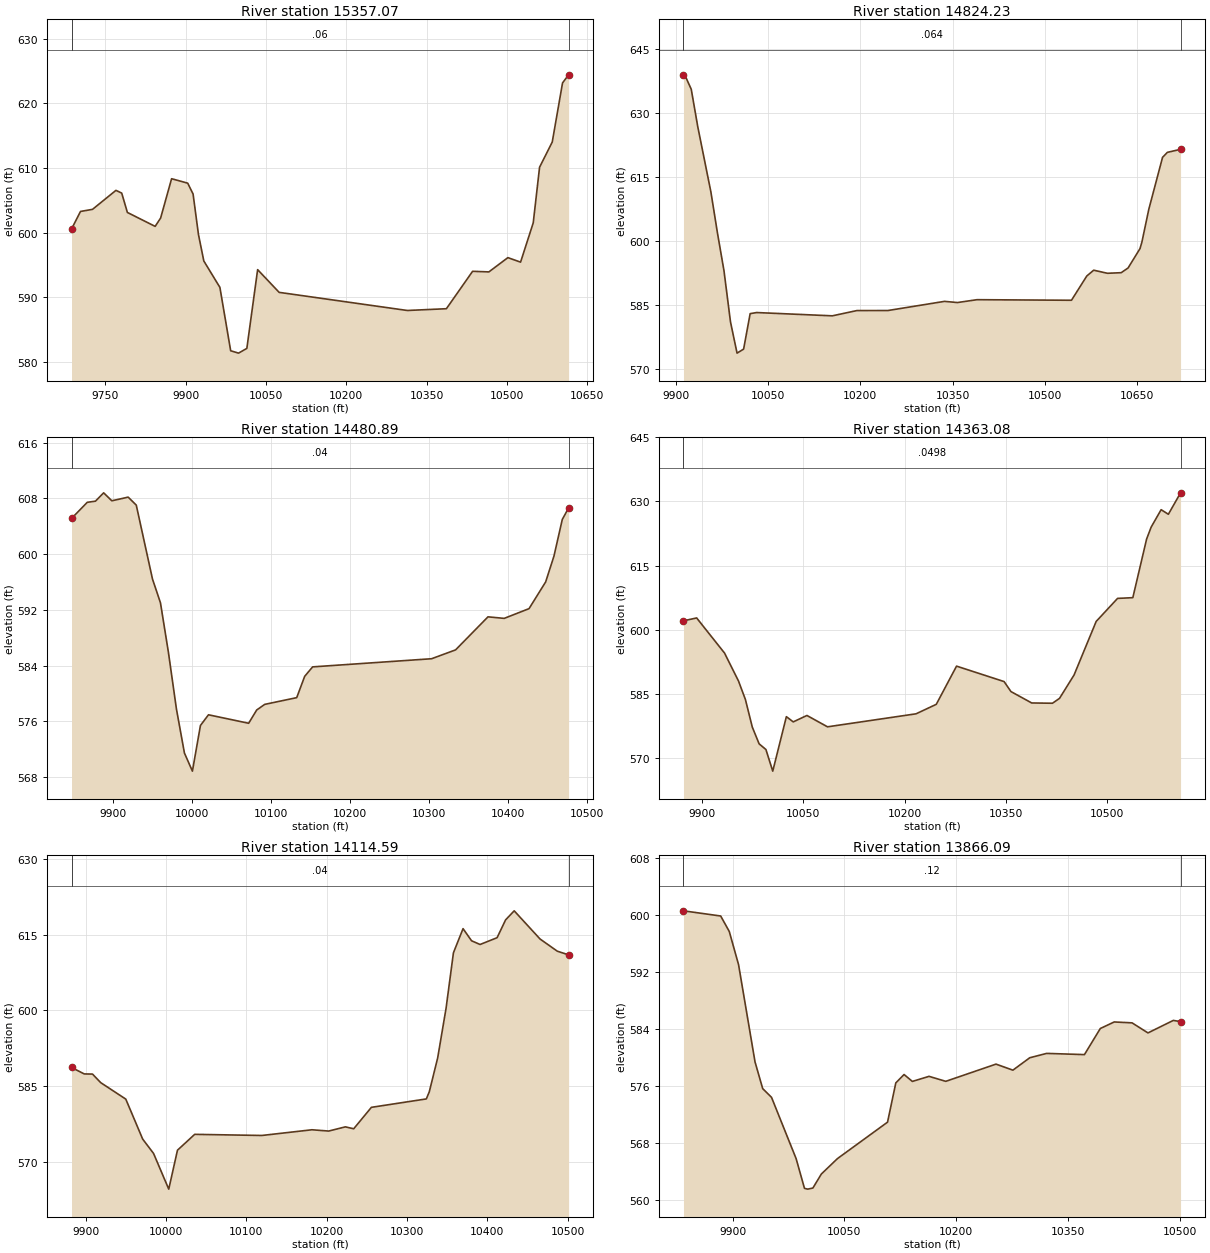
Type RM Length L Ch R = 1 ,15357.07,532.838600,532.838600,532.838600
XS GIS Cut Line= 6
559956.064519197805400.109001338560018.999414325805575.394403622
560011.728973061805816.765327469560038.901852965805922.480222762
 560123.00646022806030.115246698560330.816765994806171.050888434
#Sta/Elev= 30
9687.157600.53669703.891603.26299726.366603.59119770.106 606.531 9780.89606.1067
9791.452603.11039843.308600.95739853.536602.24649873.991608.3329 9904.09607.6451
 9914.12605.9637 9924.15599.70389934.167595.59919964.197591.51029984.311 581.701
    9999581.334310014.51582.067210034.64594.256310074.79 590.74110314.09587.9354
10387.06588.209110436.01594.0001 10466.4593.908210501.89596.117810525.55595.4181
10549.21601.503510561.04610.1107 10584.7614.012510603.92623.159910615.25624.4152
#Mann= 3 , 0 , 0
9687.157    0.06       09687.157    0.06       010615.25    0.06       0
#XS Ineff= 2 , 0
       09901.632        10054.63       0
Bank Sta=9687.157,10615.25
Exp/Cntr=0.3,0.1

Type RM Length L Ch R = 1 ,14824.23,343.346500,343.346500,343.346500
XS GIS Cut Line= 6
559553.102624893  805962.7329005559717.003244191806019.229283586
559909.667227358806036.232285976559996.584110528806060.107307687
560030.314453036806073.491282821560311.154720575806214.588274851
#Sta/Elev= 30
9912.591638.94119914.608639.0409 9925.24635.65619935.871626.84319957.135611.5968
9967.766602.00259978.398593.1295 9989.03581.08429999.661573.771810010.34574.7152
10020.97583.0343 10031.6583.287610154.56582.5189 10194.6583.757610244.73  583.76
10336.87 585.91110357.78585.6326 10389.7586.304810543.19586.1693 10568.1591.8625
10579.29593.221810601.67592.496610624.05592.637710635.24593.754310654.56598.2858
10657.63 599.80710668.82 607.478 10691.2619.684810699.11 620.86410720.47621.5636
#Mann= 3 , 0 , 0
9912.591   0.064       09912.591   0.064       010720.47   0.064       0
#XS Ineff= 2 , 0
       0                10106.95       0
Bank Sta=9912.591,10720.47
Exp/Cntr=0.3,0.1

Type RM Length L Ch R = 1 ,14480.89,117.804000,117.804000,117.804000
XS GIS Cut Line= 6
559665.725335505806279.212726352559764.218787933806254.358669646
559924.515532341806227.394645082560006.562007205806219.850583666
560139.016010701806229.120184033560282.605086893806268.659384584
#Sta/Elev= 30
9847.801605.12579867.743607.44739878.089607.61269888.435608.80829898.781607.6645
9919.436608.1909 9929.69607.04339950.187596.44129960.295593.01789970.404585.8779
  9980.5577.77579990.595571.468210000.69  568.8710010.85575.421310021.01576.9556
10071.82575.738210081.98577.641610092.14578.4488 10132.6579.415410142.67582.4731
10152.74583.830310303.14584.998410333.49586.2689 10374.5591.0115   10395590.7906
10426.39592.186110447.42596.021910457.93599.732410468.45604.985510476.44606.6465
#Mann= 3 , 0 , 0
9847.801    0.04       09847.801    0.04       010476.44    0.04       0
#XS Ineff= 2 , 0
       0                               0
Bank Sta=9847.801,10476.44
Exp/Cntr=0.3,0.1

Type RM Length L Ch R = 1 ,14363.08,248.497300,248.497300,248.497300
XS GIS Cut Line= 6
559726.115903795806387.353976503559824.609356195806362.499919787
559984.906100601806335.535895228560139.013026476806329.594315007
560271.251095831806353.517583191560441.766879767806421.039752349
#Sta/Elev= 30
9872.245602.08299891.783602.75619933.168594.53349953.734588.03599963.988583.7115
9974.236 577.2369984.345573.32559994.453571.985110004.55566.942510024.74579.6763
10034.89578.454710055.22579.9553 10085.7577.300210216.88 580.34110246.89582.5608
 10276.9591.491810347.35587.881510357.53585.542710388.29582.879510419.05582.8153
10429.49583.9547   10451589.404510483.81601.942210515.53607.328110538.13607.4991
10558.56 621.21210565.29623.992310580.07628.067710590.82 626.99910608.86632.0109
#Mann= 3 , 0 , 0
9872.245  0.0498       09872.245  0.0498       010608.86  0.0498       0
#XS Ineff= 2 , 0
       0                10289.61       0
Bank Sta=9872.245,10608.86
Exp/Cntr=0.3,0.1

Type RM Length L Ch R = 1 ,14114.59,248.497200,248.497200,248.497200
XS GIS Cut Line= 6
559739.452863306806567.593307822559783.153506704806576.680835123
559822.633099248806588.924459617559912.700298608806623.659330755
560190.042017788806703.733651031560328.168018858806754.386554068
#Sta/Elev= 30
9882.589 588.6489898.469587.37019908.683587.34189918.897585.64599950.098582.3796
9971.116 574.4589984.638571.615110003.55564.5408 10014.4572.255910035.84575.3968
10119.43575.174110181.72576.304210202.48576.048310223.24576.881410233.62 576.501
10255.63580.749510323.98582.416510327.64583.8166 10338.1590.552910348.56600.4122
10357.69611.375810369.66616.160310380.24  613.7610390.83613.0227   10412614.3669
10422.58617.899410433.28619.694410465.43614.112410486.86611.699410500.97 610.963
#Mann= 3 , 0 , 0
9882.589    0.04       09882.589    0.04       010500.97    0.04       0
#XS Ineff= 2 , 0
       0                               0
Bank Sta=9882.589,10500.97
Exp/Cntr=0.3,0.1

Type RM Length L Ch R = 1 ,13866.09,248.497300,248.497300,248.497300
XS GIS Cut Line= 6
559631.824365445806758.630693735559683.434457346806788.556590354
559799.170632844806847.702164625559902.576277752806897.248938193
 559987.91426189806940.246203969560223.585351467807065.515432876
#Sta/Elev= 30
9834.237600.54259884.146599.81749895.651597.6576 9908.14592.99889930.247579.3646
9940.502575.63649952.354574.41439985.353565.82289996.566 561.666   10001561.5574
10007.86561.713310019.16563.670710040.76565.831710107.96570.938310119.05576.4374
10130.13577.611510141.25576.645710163.64577.355310186.04576.657510253.44579.0692
10276.09578.222610298.74579.961710321.39580.570710372.06580.401110393.36584.0574
10411.99584.974610435.97584.848410457.28583.439610491.27585.190810500.99585.0234
#Mann= 3 , 0 , 0
9834.237    0.12       09834.237    0.12       010500.99    0.12       0
#XS Ineff= 2 , 0
       0                               0
Bank Sta=9834.237,10500.99
Exp/Cntr=0.3,0.1

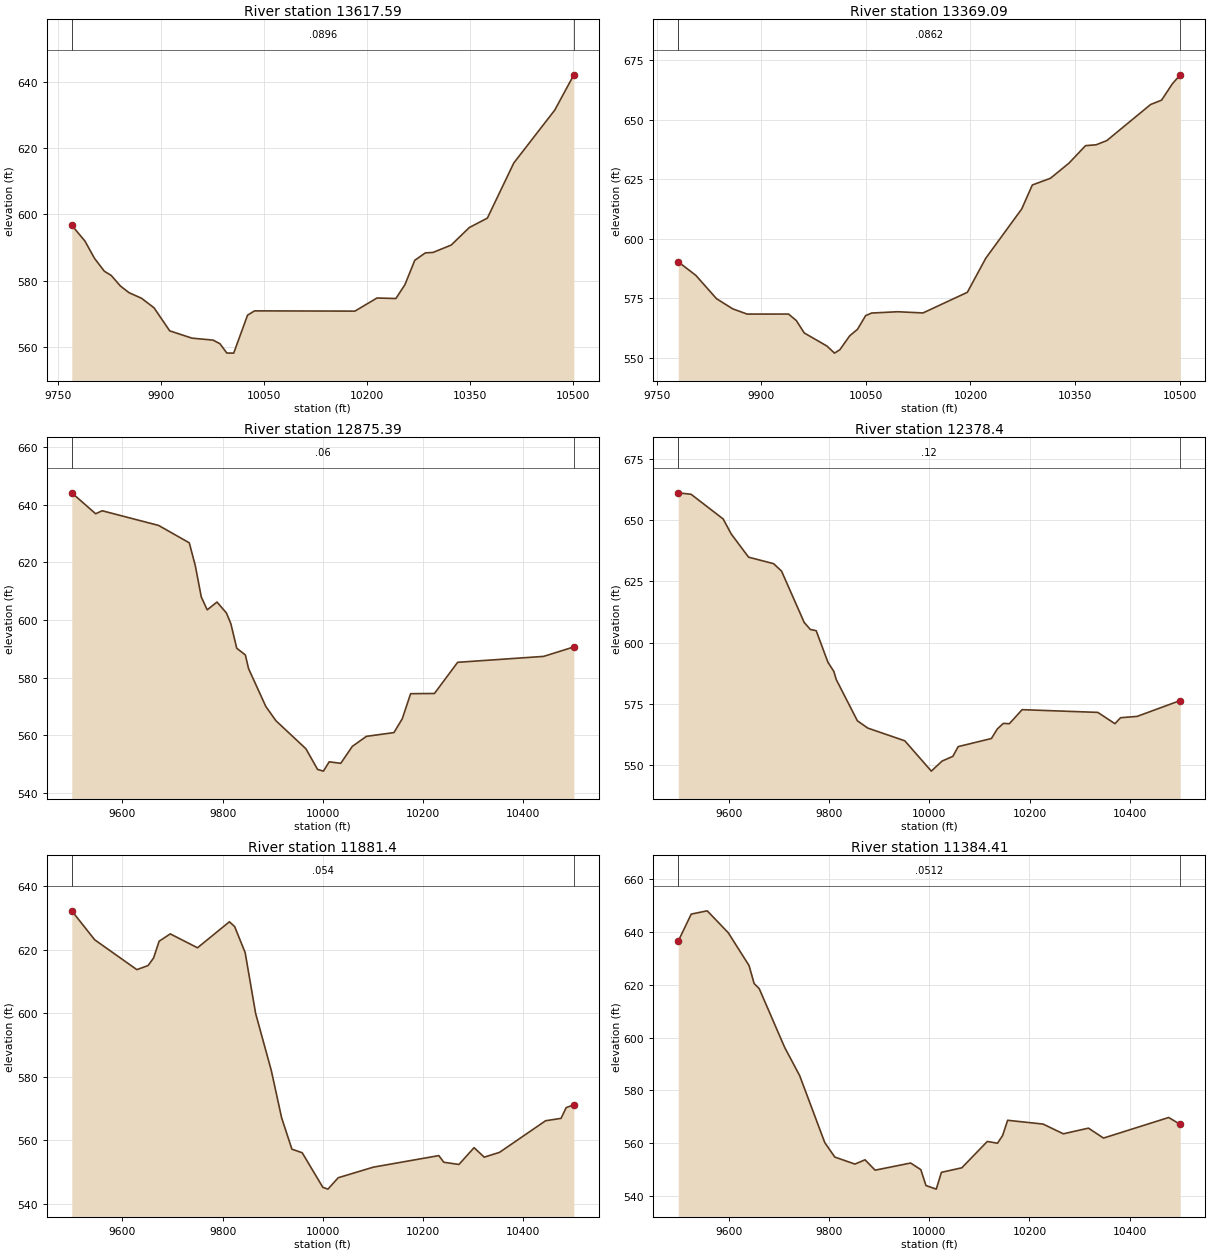
Type RM Length L Ch R = 1 ,13617.59,248.497300,248.497300,248.497300
XS GIS Cut Line= 6
559501.192753119806794.225195237559585.208556624806896.378128548
559613.906023635 807033.91871518559646.284914224807093.828766576
559757.409950093807207.117628615559933.212170772807352.284365499
#Sta/Elev= 30
9770.612596.7264 9789.77591.95529803.645586.73179817.993582.81699828.047581.5422
9841.266578.36699853.949576.31529871.896574.66199890.175571.76789913.056564.7789
9945.417562.56949976.092 561.9759986.108560.88899996.125558.060110006.13 558.034
10026.26569.516110036.44570.8248 10182.4570.745910214.53574.720810242.01574.5602
10255.12578.739110269.48586.129910284.87588.370310296.01588.512710322.41590.7317
 10348.8596.048910375.05598.895610413.47615.575410473.15631.613710500.82 642.261
#Mann= 3 , 0 , 0
9770.612  0.0896       09770.612  0.0896       010500.82  0.0896       0
#XS Ineff= 2 , 0
       0                               0
Bank Sta=9770.612,10500.82
Exp/Cntr=0.3,0.1

Type RM Length L Ch R = 1 ,13369.09,493.702500,493.702500,493.702500
XS GIS Cut Line= 6
559300.863918972807047.920667082559358.485919016807100.715765251
559414.347787244807139.552355297 559525.54250392807190.746536154
559589.357338053807230.237603452559877.291732462807472.143075264
#Sta/Elev= 30
9780.981590.24029806.263584.54689835.868574.75639859.132570.49139879.854 568.289
9939.187568.30339950.414565.53979961.641560.38229994.341554.842710005.11551.8958
10012.69553.314210026.95 559.19410038.04561.895110049.72567.648510058.33568.7318
 10095.5569.280410131.99568.774710195.55577.434810222.03591.770710273.51 612.429
10288.76622.510110314.72625.3295 10341.2631.650910365.05639.0278 10380.3639.3904
 10395.6641.168410458.36656.311310474.05658.132310489.74665.085810500.95668.7733
#Mann= 3 , 0 , 0
9780.981  0.0862       09780.981  0.0862       010500.95  0.0862       0
#XS Ineff= 2 , 0
       0                               0
Bank Sta=9780.981,10500.95
Exp/Cntr=0.3,0.1

Type RM Length L Ch R = 1 ,12875.39,496.994500,496.994500,496.994500
XS GIS Cut Line= 6
558783.802489424806978.043512707558934.307070732807178.390429016
559101.144614528807463.295231865559151.877937027807537.960971119
559255.197454658807658.220178846559379.956590632807776.639360908
#Sta/Elev= 30
9499.037644.08639546.733636.8225 9559.64637.8706  9672.3632.7777 9733.53 626.744
9745.594618.79379757.528607.93369769.317603.49879788.803606.19639807.682602.3983
9816.476 598.7119828.265590.17459845.441587.84439851.845583.10149886.239569.9925
9906.377 565.0419966.346555.28829989.569548.130110001.23547.544210012.76550.7791
10035.82550.250510058.88556.1307 10087.1559.611610141.94560.909410158.53565.6919
10175.23574.4081 10222.8574.477910269.05585.290910440.68587.346310500.95590.6308
#Mann= 3 , 0 , 0
9499.037    0.06       09499.037    0.06       010500.95    0.06       0
#XS Ineff= 2 , 0
       0                               0
Bank Sta=9499.037,10500.95
Exp/Cntr=0.3,0.1

Type RM Length L Ch R = 1 , 12378.4,496.994600,496.994600,496.994600
XS GIS Cut Line= 6
558488.753909869807305.056149312558679.826571976807566.826105942
558771.888894578807805.605893879558816.986642532807883.414565662
558913.781387253 807969.83364544559094.460810529808056.264058631
#Sta/Elev= 30
9499.071661.06299524.675660.47569588.763650.40039604.728644.31989639.413634.8201
9689.353 632.1779705.258 629.1239750.472608.18119762.586605.35059774.338604.8369
9797.842591.92479809.594588.23019814.303584.94219856.509568.09699877.196 565.126
9951.177559.930910004.05547.566910025.52551.671510046.99553.586610057.72557.5693
10123.94560.864410135.69564.748610147.75567.0264 10159.8566.915710185.23572.6331
10336.23571.522410370.49566.9098 10381.6569.346810414.59569.884110500.87576.3636
#Mann= 3 , 0 , 0
9499.071    0.12       09499.071    0.12       010500.87    0.12       0
#XS Ineff= 2 , 0
       0                10288.27       0
Bank Sta=9499.071,10500.87
Exp/Cntr=0.3,0.1

Type RM Length L Ch R = 1 , 11881.4,496.994500,496.994500,496.994500
XS GIS Cut Line= 6
557922.086196909807811.232720576558103.695675726807908.513128509
 558277.23819401 807969.17416926558412.992754793808000.908678465
 558684.05388499808024.966669933558879.886251248808065.624753124
#Sta/Elev= 30
9499.078632.17959544.856 623.0739628.939613.69459651.279614.96969662.267617.3371
9673.377622.61529695.596624.93269749.961 620.5689813.678  628.749824.138 627.219
9845.059619.0556 9865.98599.92179897.222581.99399917.784567.16019938.346557.2671
9958.908556.139410000.04545.281710010.27544.706610030.69548.284410101.12551.6235
10231.43555.244210241.48553.153110271.65552.457810301.82557.738910322.15554.7532
10352.63556.266410444.58566.199410475.38566.947610485.65570.335110500.93571.1816
#Mann= 3 , 0 , 0
9499.078   0.054       09499.078   0.054       010500.93   0.054       0
#XS Ineff= 2 , 0
       0                               0
Bank Sta=9499.078,10500.93
Exp/Cntr=0.3,0.1

Type RM Length L Ch R = 1 ,11384.41,496.994500,496.994500,496.994500
XS GIS Cut Line= 6
558120.640504632 808378.34952702558254.072050921808421.528928331
 558387.24602234808436.231434479 558546.34252424808419.981313585
 558880.38443078808362.217763186559108.092963964808362.829793181
#Sta/Elev= 30
9499.102636.61059525.036646.87479556.974648.11389598.929639.80169640.403627.3636
 9650.56620.53939660.717618.60549711.371596.36159741.454 585.5969791.506560.2126
9811.545554.71949851.669552.06169871.848553.68699892.027 549.7489962.804552.4618
9983.182549.94769993.462543.9103   10014 542.56110024.25548.928810065.02550.6545
10115.83560.639710136.15559.979610146.32562.867410156.45 568.67210227.23567.2309
10267.51563.539610317.67565.691410347.69561.9246 10477.8569.732910500.97567.0817
#Mann= 3 , 0 , 0
9499.102  0.0512       09499.102  0.0512       010500.97  0.0512       0
#XS Ineff= 2 , 0
       0                               0
Bank Sta=9499.102,10500.97
Exp/Cntr=0.3,0.1

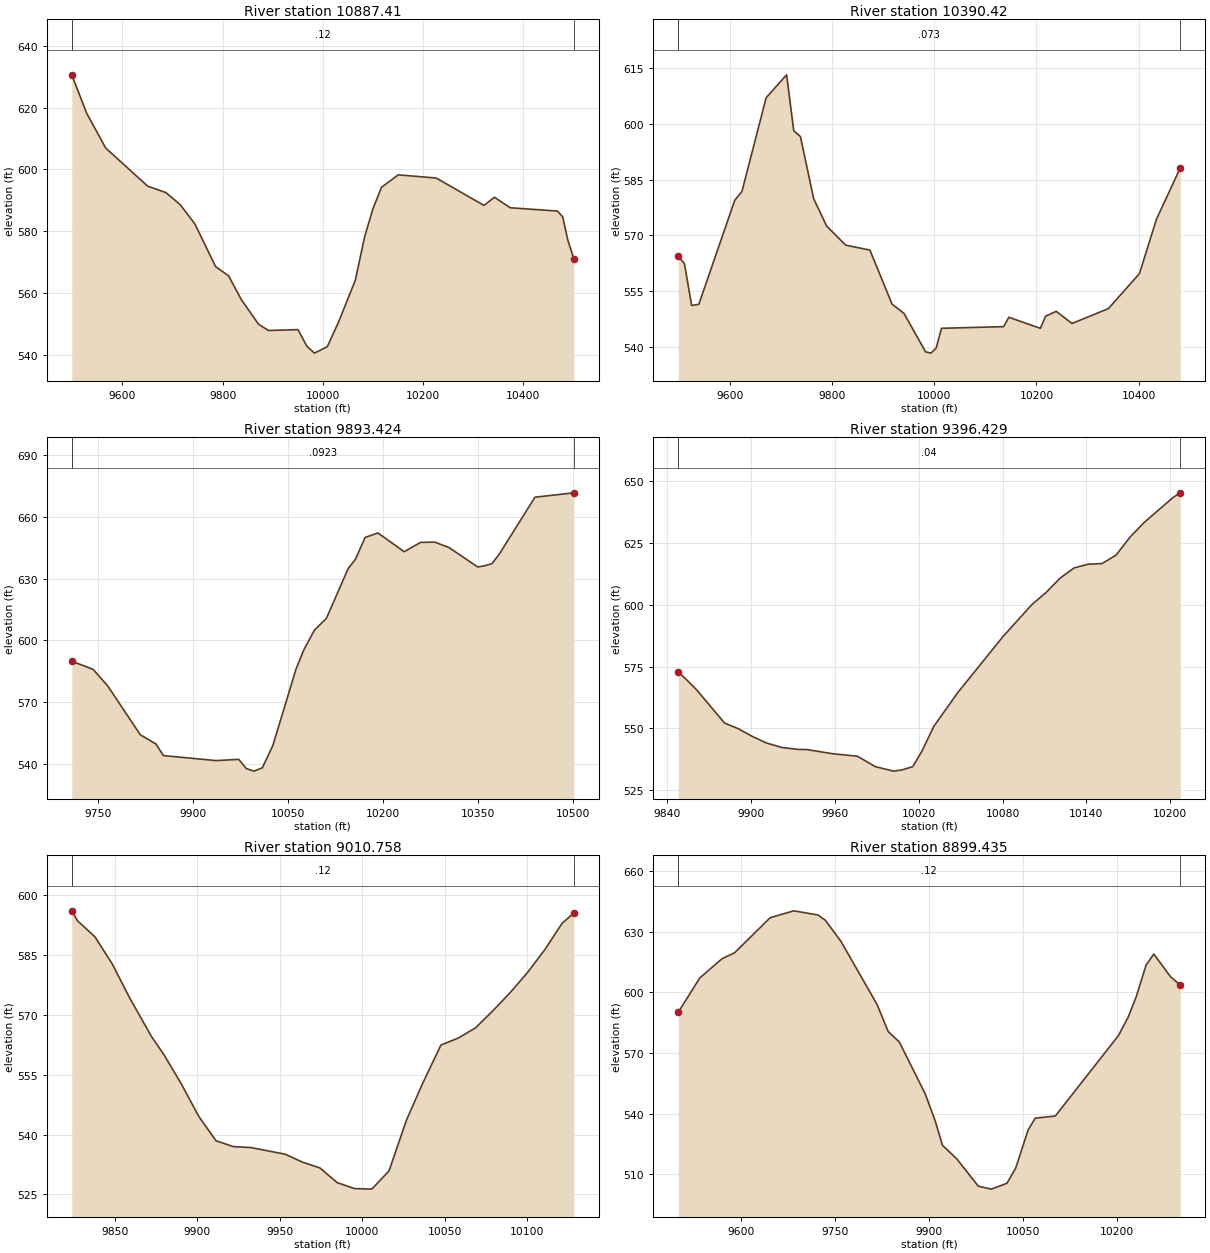
Type RM Length L Ch R = 1 ,10887.41,496.994600,496.994600,496.994600
XS GIS Cut Line= 6
 558200.50455708808502.816089676558353.945732571808630.979779862
558519.806426971808851.345548041558590.739980671808905.304872724
558725.833219203808972.490684144558996.173367767809060.179719586
#Sta/Elev= 30
9499.118630.61099529.096618.09369566.856606.87359650.784594.52039686.876592.4746
9715.501588.54949744.702582.33069786.037568.51599812.169565.45219837.397557.7949
9871.969549.80019891.614547.78939950.504548.06489968.387542.64559983.401540.4545
10008.87542.528810030.96550.328510064.93564.0917 10083.5578.161310099.79587.0906
10117.13594.185310150.58   598.210226.37597.181310321.54588.313810342.57590.9417
10373.99587.546910468.26586.479310478.74584.589710489.21576.856210500.91571.0352
#Mann= 3 , 0 , 0
9499.118    0.12       09499.118    0.12       010500.91    0.12       0
#XS Ineff= 2 , 0
       0                               0
Bank Sta=9499.118,10500.91
Exp/Cntr=0.3,0.1

Type RM Length L Ch R = 1 ,10390.42,496.994500,496.994500,496.994500
XS GIS Cut Line= 6
557683.377744053808716.339443571 557888.11706575808909.994358099
558042.676479364 808998.51611499558145.465302897809024.859023471
558435.182928247808976.598593047558545.562933254809019.720075653
#Sta/Elev= 30
9499.115564.33449511.291562.37299525.349551.13559539.407551.43799609.698579.4515
9623.756581.79419671.128607.05499711.181613.22429725.248598.13229738.216596.6111
9764.151579.87149789.689572.4716 9826.86567.36549874.182 566.0519917.476551.5163
9940.895548.99929983.191538.64429993.578538.301110003.91539.664410014.27544.9826
10135.92545.430110146.09547.945810207.72544.978210218.06548.246310238.75549.5577
10269.79546.287210340.88550.282410401.75559.723110434.75574.265410481.64588.1902
#Mann= 3 , 0 , 0
9499.115   0.073       09499.115   0.073       010481.64   0.073       0
#XS Ineff= 2 , 0
       0                               0
Bank Sta=9499.115,10481.64
Exp/Cntr=0.3,0.1

Type RM Length L Ch R = 1 ,9893.424,496.994500,496.994500,496.994500
XS GIS Cut Line= 6
 558146.77517702809231.936943764 558270.58130607809145.426786089
558348.941922603809133.660831811 558413.61152984 809201.34592197
558467.574815414809240.773462872558819.319221845809429.804488081
#Sta/Elev= 30
9707.888589.93569741.685586.01579765.008577.81639816.135554.28499840.835549.8086
9852.678544.1741 9935.82541.7532 9971.62542.35349983.836 537.7979995.917  536.64
10008.94538.2653 10025.5549.062810062.16586.203910074.39 595.41110091.23605.0789
10110.11610.739310144.56 634.93710156.04639.434210171.19649.965810191.53652.1656
10233.04643.048410258.73 647.58110281.33647.715610303.93645.055810349.14635.6595
10360.44636.275810371.74637.305510383.04641.840710439.55669.509110500.94671.6258
#Mann= 3 , 0 , 0
9707.888  0.0923       09707.888  0.0923       010500.94  0.0923       0
#XS Ineff= 2 , 0
       0                               0
Bank Sta=9707.888,10500.94
Exp/Cntr=0.3,0.1

Type RM Length L Ch R = 1 ,9396.429,385.671800,385.671800,385.671800
XS GIS Cut Line= 6
558148.817271002809302.821274621558149.395806693809379.805429334
558072.797296731809453.743580022558053.124135568809490.453074135
558044.863407955809539.113957208558055.513816755809620.069060402
#Sta/Elev= 30
9847.787572.99169860.537565.86829880.905 552.1949890.953549.82349900.954 546.709
9911.104544.06169921.973542.29389933.681541.48839939.684541.44899958.478539.7428
 9976.14538.72439989.035 534.50410002.05532.707110008.34533.235410015.74534.5296
10022.42540.907310030.75550.792310048.24 564.68810080.57587.319110101.13600.1612
10111.18 605.00610121.23 610.79510131.26614.930810141.26616.426610151.27616.6968
10161.32620.117310171.47627.503910181.62633.422610202.03643.403310207.31645.3143
#Mann= 3 , 0 , 0
9847.787    0.04       09847.787    0.04       010207.31    0.04       0
#XS Ineff= 2 , 0
       0                               0
Bank Sta=9847.787,10207.31
Exp/Cntr=0.3,0.1

Type RM Length L Ch R = 1 ,9010.758,111.322800,111.322800,111.322800
XS GIS Cut Line= 2
 557790.32564263809291.605090782557882.952668026809581.803590655
#Sta/Elev= 30
9823.752596.08689827.316593.56279837.813589.5752 9848.31582.77419858.807574.3195
9872.012564.65519879.801559.95189890.298552.64919900.795  544.579911.292538.4485
9921.789536.98969932.286536.7638 9953.28535.08579963.777533.09259974.274531.6498
9984.771527.97139995.268526.471610005.77526.333910016.26 530.92210026.76543.5731
10036.45552.671310047.75562.456810058.25564.192110068.75566.763510079.24571.0317
10089.74575.593110100.24580.617110110.74586.335610121.23592.946810128.37595.5386
#Mann= 3 , 0 , 0
9823.752    0.12       09823.752    0.12       010128.37    0.12       0
#XS Ineff= 2 , 0
       0                               0
Bank Sta=9823.752,10128.37
Exp/Cntr=0.3,0.1

Type RM Length L Ch R = 1 ,8899.435,496.994500,496.994500,496.994500
XS GIS Cut Line= 6
557477.065617779809055.868995073557669.145308803809362.677397714
557792.959840619809586.266875059557814.794455187809617.689202068
 557846.80163397809655.899506568557916.624824224809721.782104523
#Sta/Elev= 30
 9499.02590.09249533.389607.10869568.783616.60679589.352619.68179645.887636.9731
9683.577640.35949722.158638.29349733.956635.68799758.958625.19759816.543593.9699
9834.338580.55929851.937575.4507 9893.47549.67439909.489536.25639920.948524.2576
9943.864517.52719978.239504.0157    9999502.552710023.94505.454910037.98513.0152
10057.81531.8846 10069.1537.704410101.17538.745710201.92578.561110217.67587.7911
10230.32597.749510246.11  613.4810258.45618.946110285.33607.657210300.77603.5934
#Mann= 3 , 0 , 0
 9499.02    0.12       0 9499.02    0.12       010300.77    0.12       0
#XS Ineff= 2 , 0
       0                               0
Bank Sta=9499.02,10300.77
Exp/Cntr=0.3,0.1