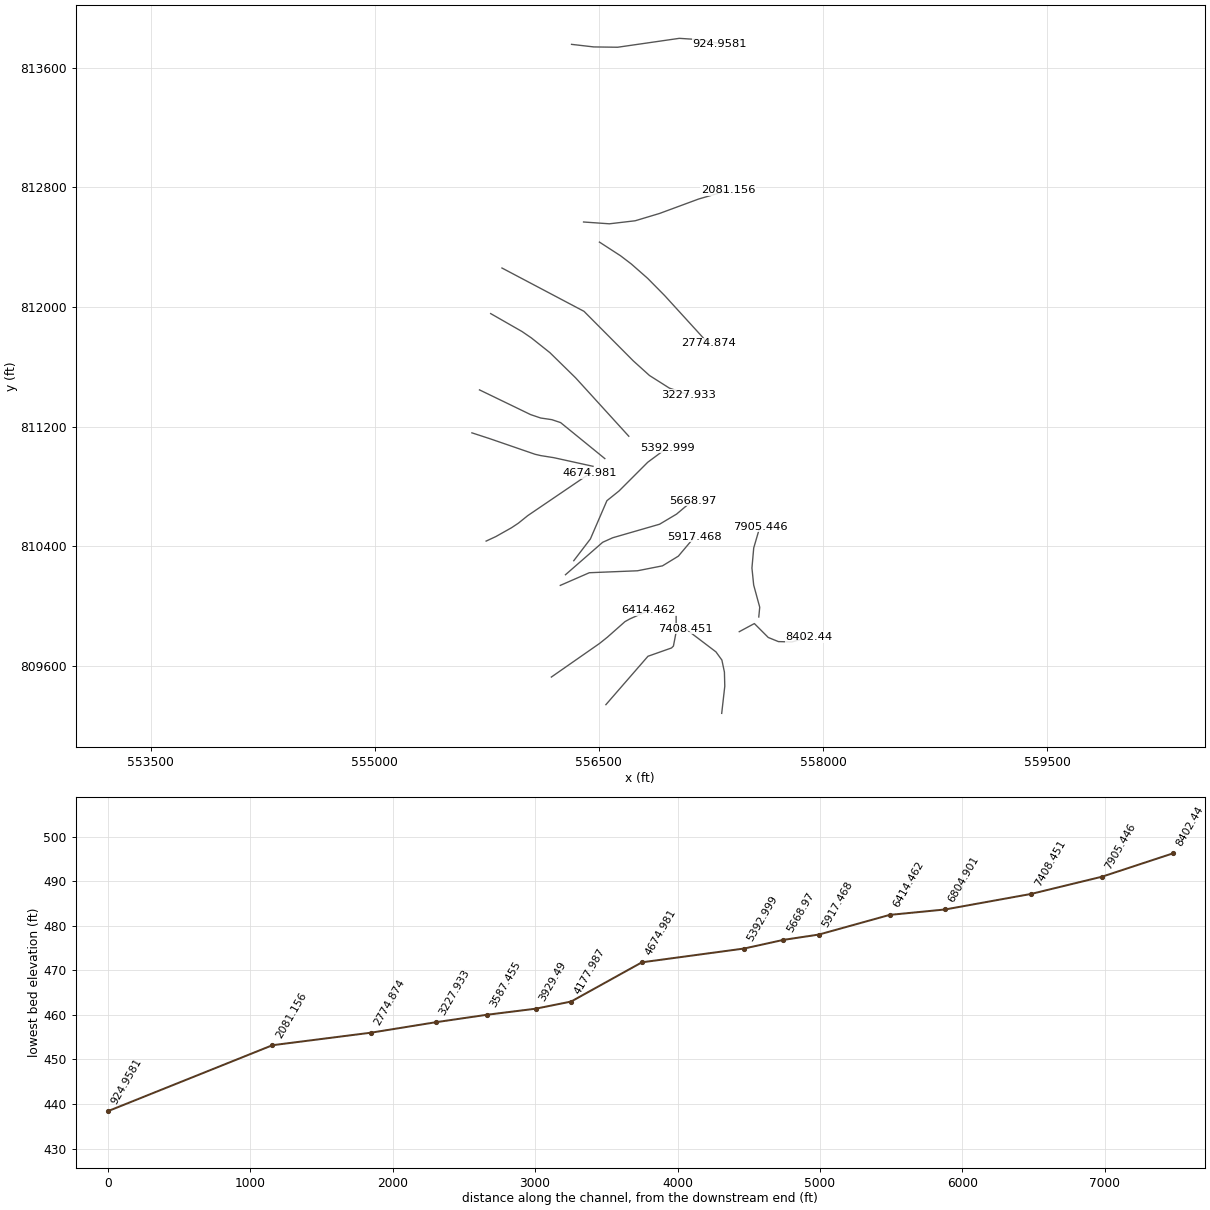
HEC-RAS study 11038_ras.prj: 11038

--- 11038_ras.g01 (geometry) --- (continued)

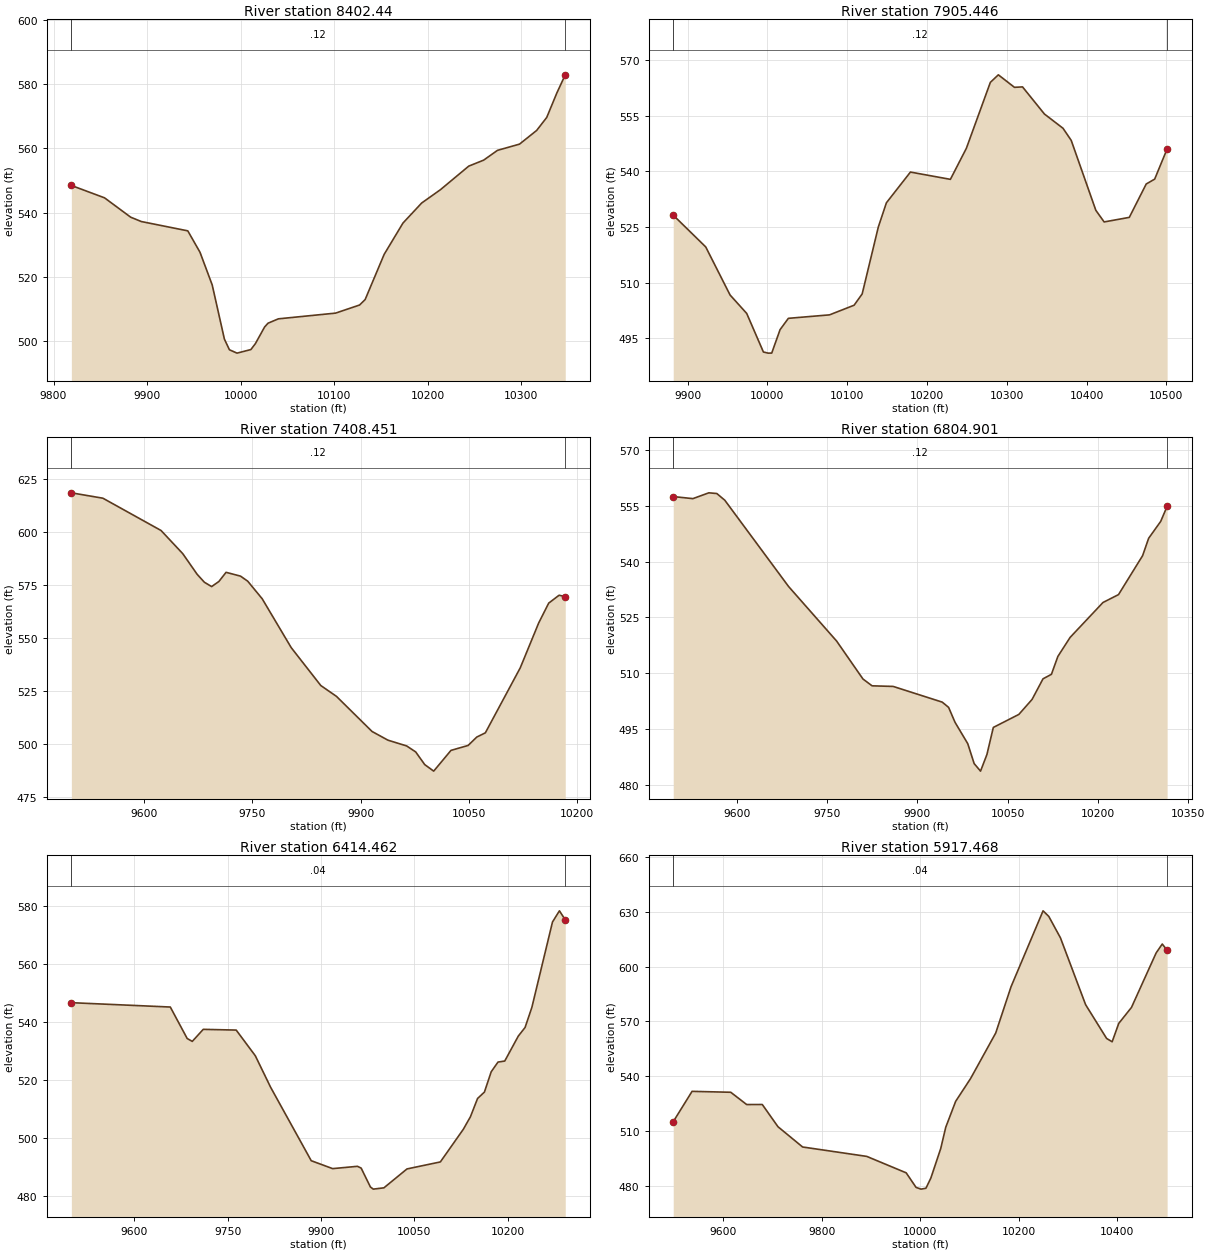
Type RM Length L Ch R = 1 , 8402.44,496.994600,496.994600,496.994600
XS GIS Cut Line= 6
557439.091648877809828.191347376557540.093323141 809882.53241542
557633.267402887809789.453695893557701.053451777809761.942209974
  557791.7171143809759.670758724557903.415165603809792.233617172
#Sta/Elev= 30
9819.055548.46939854.532 544.6199882.542538.58519893.897537.23649943.577534.3406
9956.627527.68059969.677517.51939982.727500.65139988.077497.33049996.221496.2778
10011.04497.386110015.79499.198510025.74504.418610029.42505.597810040.45  506.95
10101.64508.731610127.32511.257610133.25512.9514 10153.6527.027510173.73536.7735
10193.74543.012910213.79547.154310244.06554.486610259.98 556.34810274.74559.3917
10298.33561.3337 10316.7565.598110327.46569.644610338.22577.221410347.27582.9073
#Mann= 3 , 0 , 0
9819.055    0.12       09819.055    0.12       010347.27    0.12       0
#XS Ineff= 2 , 0
       0                               0
Bank Sta=9819.055,10347.27
Exp/Cntr=0.3,0.1

Type RM Length L Ch R = 1 ,7905.446,496.994500,496.994500,496.994500
XS GIS Cut Line= 6
557569.703808129809926.501574755557576.013352185809991.831572622
557535.497088403810140.393277183557523.948770285810254.036858469
557535.784885049810387.790716812557577.285319567810529.728462651
#Sta/Elev= 30
9882.067528.2193 9922.79 519.6629953.276506.71189974.162501.73469995.047491.3502
   10001491.048710005.48491.0613 10015.9497.360910026.31500.423110077.94501.3602
10108.68503.959610118.79506.996710139.01525.021710149.13531.547710179.25539.8345
10229.33537.873410249.34546.239710279.37563.9989 10289.4566.036510309.59562.6662
10319.69562.786310347.14555.475110370.45551.6287 10380.7548.372310411.54529.5345
10421.94526.396910453.47527.627410474.67536.618910485.26537.933510500.87546.0804
#Mann= 3 , 0 , 0
9882.067    0.12       09882.067    0.12       010500.87    0.12       0
#XS Ineff= 2 , 0
       0                               0
Bank Sta=9882.067,10500.87
Exp/Cntr=0.3,0.1

Type RM Length L Ch R = 1 ,7408.451,603.549800,603.549800,603.549800
XS GIS Cut Line= 6
557321.586245029809282.018311362557342.217132673809463.283306185
557339.751658554809558.215931998 557322.78838887809638.523246227
557283.118488146809693.250882126557079.569709171809847.473040017
#Sta/Elev= 30
9499.127618.48239542.794615.94839623.379600.7179 9653.44589.7969 9673.48580.0151
9683.497576.27479693.497574.25299703.497576.63839713.498580.97239733.498579.1806
9743.505576.79249763.539568.50139803.773545.43759844.736527.56959866.465522.4497
9915.779505.88419937.835501.78259963.744499.0612 9976.23496.24349988.716490.2789
10001.17487.183410025.12496.965210048.88499.297210060.84503.248510072.75505.2548
 10121.1 535.91210146.67557.094110160.53566.442410174.94570.174910183.47 569.498
#Mann= 3 , 0 , 0
9499.127    0.12       09499.127    0.12       010183.47    0.12       0
#XS Ineff= 2 , 0
       0                               0
Bank Sta=9499.127,10183.47
Exp/Cntr=0.3,0.1

Type RM Length L Ch R = 1 ,6804.901,390.439300,390.439300,390.439300
XS GIS Cut Line= 6
556546.724708009809340.359241676556828.163807243809663.872824445
556985.699102928809719.374152945 556998.57661543809732.207008431
557017.357779265 809829.26333733557016.494094664809935.680599185
#Sta/Elev= 30
9494.777557.44969527.422556.89539553.918558.45549567.166558.26689580.414556.4677
9686.398533.27669766.141518.62859809.804508.44979824.973506.60889860.045506.4449
9941.506502.22879952.108500.81349962.711496.81899983.916491.05889994.518485.7156
10005.12483.691710015.72488.153910026.33495.425910068.74498.928910090.68502.9488
10108.86 508.48810122.84509.700710133.56514.5112 10153.9519.620910208.48528.9972
10234.24531.110210274.27541.576610284.28546.2358 10304.3550.779310314.99554.8342
#Mann= 3 , 0 , 0
9494.777    0.12       09494.777    0.12       010314.99    0.12       0
#XS Ineff= 2 , 0
       0                               0
Bank Sta=9494.777,10314.99
Exp/Cntr=0.3,0.1

Type RM Length L Ch R = 1 ,6414.462,496.994500,496.994500,496.994500
XS GIS Cut Line= 6
556181.757469443809524.907524762556504.504465644809749.745413452
556556.133084675809790.981097449556674.549673386809895.607827666
556708.012936814809914.103609612556833.393239357809970.222469544
#Sta/Elev= 30
9499.024546.65369657.933545.15599685.053 534.317 9693.21533.32629710.848537.4754
9763.763537.22239794.481528.37269819.108517.5008 9884.25492.25339918.613489.5253
9958.457490.31879964.438489.70119979.319483.19399983.933482.4662   10001482.9139
10038.04489.416310091.63491.829910128.52 503.07310139.95507.393210151.37513.6694
10162.42515.887510173.29522.864810184.17526.203310195.05526.5665 10216.8535.1503
10227.68538.119610238.56545.009910271.73 574.44510282.87578.278510292.22575.1828
#Mann= 3 , 0 , 0
9499.024    0.04       09499.024    0.04       010292.22    0.04       0
#XS Ineff= 2 , 0
       0                               0
Bank Sta=9499.024,10292.22
Exp/Cntr=0.3,0.1

Type RM Length L Ch R = 1 ,5917.468,248.497300,248.497300,248.497300
XS GIS Cut Line= 6
556241.681935104810137.755889995556435.697883211 810222.40707708
556757.765486229810235.462252699556925.393169684810268.486743342
557031.560892226810333.249282129557141.030091452  810462.9794404
#Sta/Elev= 30
 9499.09514.99649537.292531.6301 9615.75531.13519648.044524.40619679.717524.4308
9711.607 512.2359761.513501.14279891.603495.9933 9971.63486.97859991.643479.0017
10001.65478.052410011.67478.528610021.69484.135510041.77500.376510051.84511.9279
10071.97526.155710102.26538.669610153.23563.599210184.36588.996610249.29630.5658
10260.87627.512310284.55615.753210335.61579.112910378.14560.640910389.41 558.807
 10402.8568.8795 10428.6577.615810478.62607.474710491.03612.368210500.94609.0175
#Mann= 3 , 0 , 0
 9499.09    0.04       0 9499.09    0.04       010500.94    0.04       0
#XS Ineff= 2 , 0
       0                               0
Bank Sta=9499.09,10500.94
Exp/Cntr=0.3,0.1

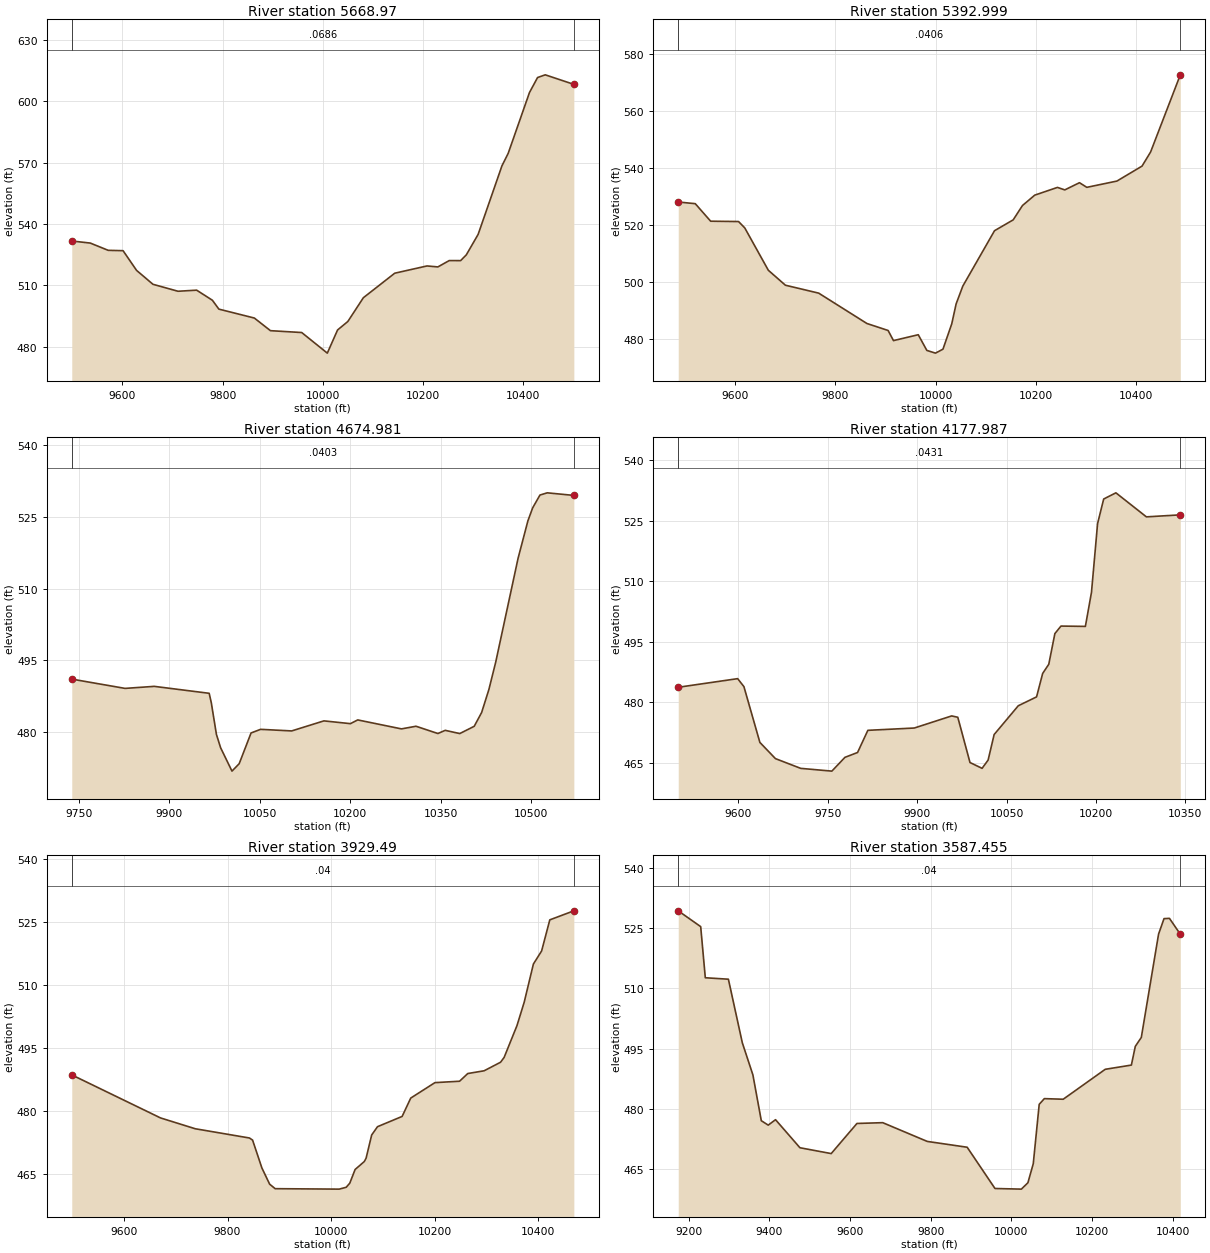
Type RM Length L Ch R = 1 , 5668.97,275.971200,275.971200,275.971200
XS GIS Cut Line= 6
 556276.27463157810209.077097517556525.264834773810426.105465255
556592.351677546810456.238635198556905.947685085 810546.82111112
557019.664847836810614.471736443 557124.99111953810703.227746256
#Sta/Elev= 30
9499.096531.66799536.043530.65039571.763527.10789601.483526.92899628.386517.3047
9661.078510.50549711.085507.09829748.263507.63639779.648502.71339792.655498.3644
9863.371 494.0119895.567487.82939957.894486.9283   10009476.859910029.44488.1676
10049.96492.328110080.92503.936310143.53 515.92310207.94519.473610229.59 518.994
10252.26522.096410274.98 522.06910286.33524.893310309.92 534.89410357.47568.4234
10369.87574.489810412.35604.209610428.49611.554910443.85612.882310500.89608.2219
#Mann= 3 , 0 , 0
9499.096  0.0686       09499.096  0.0686       010500.89  0.0686       0
#XS Ineff= 2 , 0
       0                               0
Bank Sta=9499.096,10500.89
Exp/Cntr=0.3,0.1

Type RM Length L Ch R = 1 ,5392.999,718.017800,718.017800,718.017800
XS GIS Cut Line= 6
556331.674677604810302.826996928556442.967077562810448.340683255
556553.469625078810704.090166878 556634.39987359 810768.99306307
556826.807807404810961.240243699556957.582632223 811057.87706826
#Sta/Elev= 30
9486.208528.04189520.183527.45989550.887521.29379606.596521.17719618.967518.9384
9666.012504.04359700.075498.79299766.462496.00779862.662485.33579905.027482.8767
9915.672479.32039965.137481.38669982.257475.87049999.497474.918210014.45476.3107
10031.94485.2026 10040.7492.222310054.05498.484810117.33517.956810154.52521.7623
 10173.1526.807210197.57530.455210242.88533.175510257.52532.298110286.82534.8301
10301.46533.200810361.56535.407110411.66540.664210428.74545.622410488.02572.7523
#Mann= 3 , 0 , 0
9486.208  0.0406       09486.208  0.0406       010488.02  0.0406       0
#XS Ineff= 2 , 0
       0                               0
Bank Sta=9486.208,10488.02
Exp/Cntr=0.3,0.1

Type RM Length L Ch R = 1 ,4674.981,496.994600,496.994600,496.994600
XS GIS Cut Line= 6
555745.299687369810434.012216601555809.859880593810463.948196376
555915.280853182810523.294606972555960.800059259810553.532643376
556024.206220824810604.501224618556441.520239949810887.786016196
#Sta/Elev= 30
9738.054491.06199826.396489.1202 9874.85489.54359965.925488.09249969.473486.1003
 9977.93479.49989984.894476.706610003.73 471.81810015.67473.367410035.39479.8012
10051.21480.557110102.75480.223710156.17482.325110200.16481.745810212.25482.5265
10284.77480.651410308.94481.2031 10345.2479.682510357.29480.346710381.46479.6719
10405.43481.193410417.72484.0771 10429.8488.901410441.04494.588810478.15516.3234
10494.46 524.16110502.32526.863910514.41529.5473 10526.5530.016910570.64529.4751
#Mann= 3 , 0 , 0
9738.054  0.0403       09738.054  0.0403       010570.64  0.0403       0
#XS Ineff= 2 , 0
       0                               0
Bank Sta=9738.054,10570.64
Exp/Cntr=0.3,0.1

Type RM Length L Ch R = 1 ,4177.987,248.497200,248.497200,248.497200
XS GIS Cut Line= 6
555650.208715509811157.724038477555768.950391284811119.002484768
556073.059264473811014.354580087556111.284068561811005.495125293
556198.190772614810991.680857828556460.560911506810934.027647182
#Sta/Elev= 30
 9499.03483.75849598.734485.89249609.253483.91759636.012470.11569662.131466.1017
9704.524463.69169756.796463.0072 9778.71466.41549799.906467.61749817.189473.1027
9895.098473.67419957.815476.6697 9968.08476.33619988.565465.133510008.83463.6964
10018.95  465.7410029.07472.064410069.56479.182710100.24481.380710110.48487.1789
10120.72489.444510130.96497.0386 10141.2498.903910182.15498.823310192.39507.2637
10202.63524.273910212.87530.345810233.35531.878410284.54525.929510341.42526.4256
#Mann= 3 , 0 , 0
 9499.03  0.0431       0 9499.03  0.0431       010341.42  0.0431       0
#XS Ineff= 2 , 0
       09887.592                       0
Bank Sta=9499.03,10341.42
Exp/Cntr=0.3,0.1

Type RM Length L Ch R = 1 , 3929.49,342.034400,342.034400,342.034400
XS GIS Cut Line= 6
555700.805302709811444.989400345556043.076742415811279.646317155
556110.145995057811256.981325186556185.398118582811245.778185912
556243.737209199811226.167002492556539.443693757810985.709470063
#Sta/Elev= 30
9499.043488.58529670.531478.34169737.575475.76729842.172473.57169848.341473.0703
9866.286466.4523 9881.25462.59619891.932461.508410015.67461.403710029.22461.8448
10036.09462.811810046.43466.077310064.18467.969110067.63468.764510078.41474.2844
10089.68476.257110137.23478.6982 10153.9483.065710200.63486.740810248.18487.0704
10264.03488.902710295.68489.557610327.43491.594210334.34492.754710359.13500.3157
10373.01505.853610390.83514.957910406.68518.057710422.53525.464310468.96527.6128
#Mann= 3 , 0 , 0
9499.043    0.04       09499.043    0.04       010468.96    0.04       0
#XS Ineff= 2 , 0
       0                               0
Bank Sta=9499.043,10468.96
Exp/Cntr=0.3,0.1

Type RM Length L Ch R = 1 ,3587.455,359.521900,359.521900,359.521900
XS GIS Cut Line= 6
555775.601876536811955.145100512555985.604182975811835.101972063
556048.485184052811792.059801896556172.159030633811693.750260019
  556343.8390219811525.705448424556699.923185025811135.051984011
#Sta/Elev= 30
9174.073529.30569229.777 525.3719241.226512.64919298.471 512.2889333.059496.4471
9359.234488.48159380.091477.07339397.257475.97169415.364477.32579475.934470.3419
9553.434468.89029617.288 476.3849681.227476.58359791.658471.91549890.633470.4681
9959.628460.199510025.06460.043310041.27461.632110054.55466.367910069.29481.1467
10082.04 482.56410128.81482.415210233.11489.865310297.89490.9157 10307.6495.5746
 10322.5497.790210365.34523.512310378.83527.364510392.32527.431210419.23 523.489
#Mann= 3 , 0 , 0
9174.073    0.04       09174.073    0.04       010419.23    0.04       0
#XS Ineff= 2 , 0
       0                               0
Bank Sta=9174.073,10419.23
Exp/Cntr=0.3,0.1

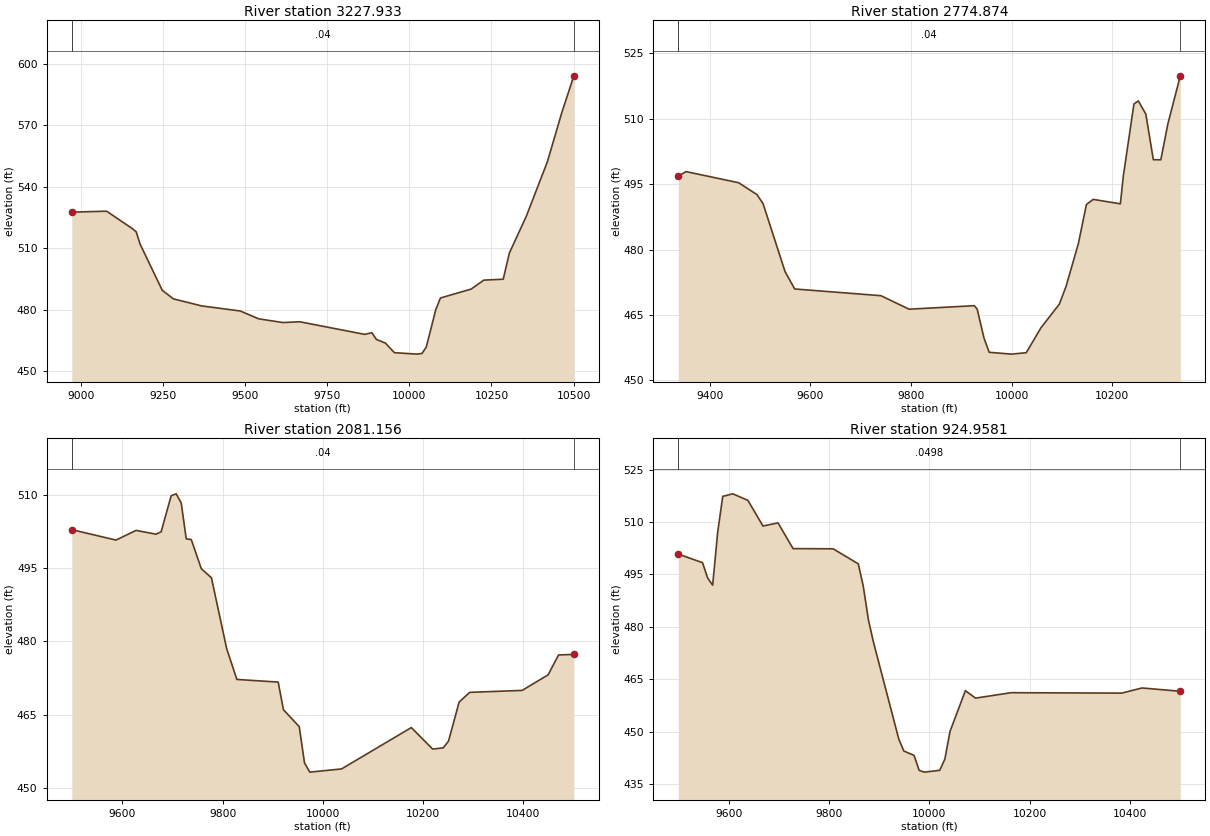
Type RM Length L Ch R = 1 ,3227.933,453.059000,453.059000,453.059000
XS GIS Cut Line= 6
555851.154549748812259.881061748556400.141281486811970.270946249
 556730.41795665811638.539459512556838.387086987811541.116737768
556971.626611561811456.710225433557100.995872438811412.202648804
#Sta/Elev= 30
8971.291527.63689077.394528.10669156.537519.53139167.843 517.9639179.149512.1346
9246.986489.50399280.905485.32279367.528481.87729484.416479.41899540.947475.5806
9614.892473.76389665.581 474.1599864.008     4689885.546468.82219899.284465.5269
9926.761463.75879954.239459.080910023.34458.365410038.27458.6917 10051.3461.8206
10080.45480.1357 10094.5485.761610188.29490.111410226.59 494.46510285.75494.9189
10304.42507.6579 10356.3525.716310420.43552.265910463.61575.880910500.92594.1432
#Mann= 3 , 0 , 0
8971.291    0.04       08971.291    0.04       010500.92    0.04       0
#XS Ineff= 2 , 0
       0                               0
Bank Sta=8971.291,10500.92
Exp/Cntr=0.3,0.1

Type RM Length L Ch R = 1 ,2774.874,693.718500,693.718500,693.718500
XS GIS Cut Line= 6
  556503.4983769812433.154845407556644.797203802812341.614628455
556716.577476461812286.935723246556825.831121635812190.973173036
 556940.15104165812075.260274984557231.000656517 811756.65311844
#Sta/Elev= 30
9337.114  496.849352.617497.89819457.291495.34189493.646492.62119505.773 490.544
9549.439474.96899568.627470.97199740.071 469.4319796.059466.3315 9925.77467.1388
9931.443466.3587 9945.05459.69979955.262456.44589999.499 456.02510028.99456.3476
10058.48462.112310094.68467.467410108.17471.571710132.65481.400910148.64490.3553
10162.13491.5239 10216.1490.503310222.05496.924510243.08513.407410251.84514.1194
10266.74511.093110281.64500.631210296.54500.606410310.53508.835810335.28519.8696
#Mann= 3 , 0 , 0
9337.114    0.04       09337.114    0.04       010335.28    0.04       0
#XS Ineff= 2 , 0
       0                               0
Bank Sta=9337.114,10335.28
Exp/Cntr=0.3,0.1

Type RM Length L Ch R = 1 ,2081.156,1156.197600,1156.197600,1156.197600
XS GIS Cut Line= 6
556397.246606644812567.533159957556569.940429752812555.439279073
556742.732230866812575.746329886556905.527394004812624.573855051
557167.858631962812721.355316135557364.424918667812778.411707432
#Sta/Elev= 30
9499.072502.88569587.349500.75619627.398502.73879667.407501.96129677.418502.4598
9697.455509.83839707.473510.23249717.492508.36229727.511501.00239737.529500.8682
9757.596494.8818 9777.78493.03729808.168478.51989828.542472.19569911.014471.6557
 9921.49465.98819953.007462.52589963.513455.10369974.018453.202510037.48453.8592
10176.69462.332110219.15457.927210240.32458.177110250.91459.562110272.08467.5598
10293.25  469.5510397.85469.949610449.71473.145510470.46477.214110500.98477.3226
#Mann= 3 , 0 , 0
9499.072    0.04       09499.072    0.04       010500.98    0.04       0
#XS Ineff= 2 , 0
       0                               0
Bank Sta=9499.072,10500.98
Exp/Cntr=0.3,0.1

Type RM Length L Ch R = 1 ,924.9581,231.239500,231.239500,231.239500
XS GIS Cut Line= 6
556316.934328113813755.262955603556465.672558181813738.124623433
 556625.27298411813735.995839813557038.076286615813795.550884234
557175.201781064813786.585021113557309.741714053813760.381230724
#Sta/Elev= 30
9499.052500.84819547.549498.38589557.639494.03299567.729491.94069577.819507.1738
9587.886 517.3849607.969518.11089638.092516.24049668.154508.88849698.182509.7829
 9728.21502.41629808.221502.35589858.357498.04519868.401  491.569878.486482.0616
9888.571475.64739939.093447.86219949.269444.4281 9969.62443.1676 9979.86438.8795
9990.113438.377110020.87438.890610031.12 442.12610041.36450.034410072.05461.7124
10092.34459.582410163.09461.131110383.92461.011310424.52462.487610500.93461.5385
#Mann= 3 , 0 , 0
9499.052  0.0498       09499.052  0.0498       010500.93  0.0498       0
#XS Ineff= 2 , 0
       0                               0
Bank Sta=9499.052,10500.93
Exp/Cntr=0.3,0.1