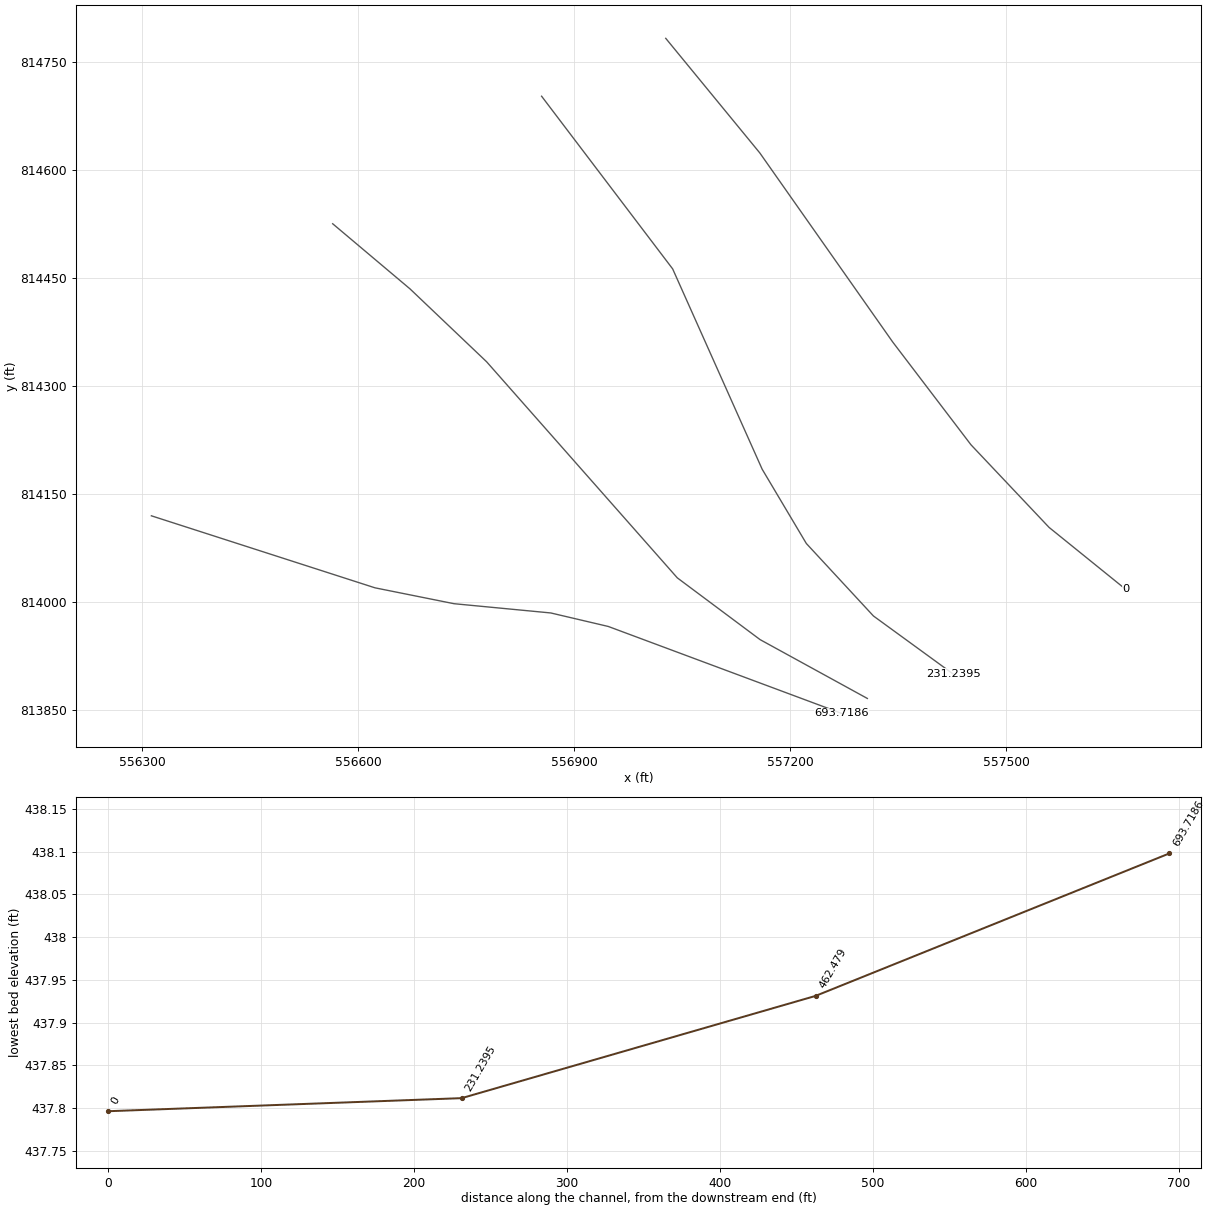
HEC-RAS study 11038_ras.prj: 11038

--- 11038_ras.g01 (geometry) --- (continued)

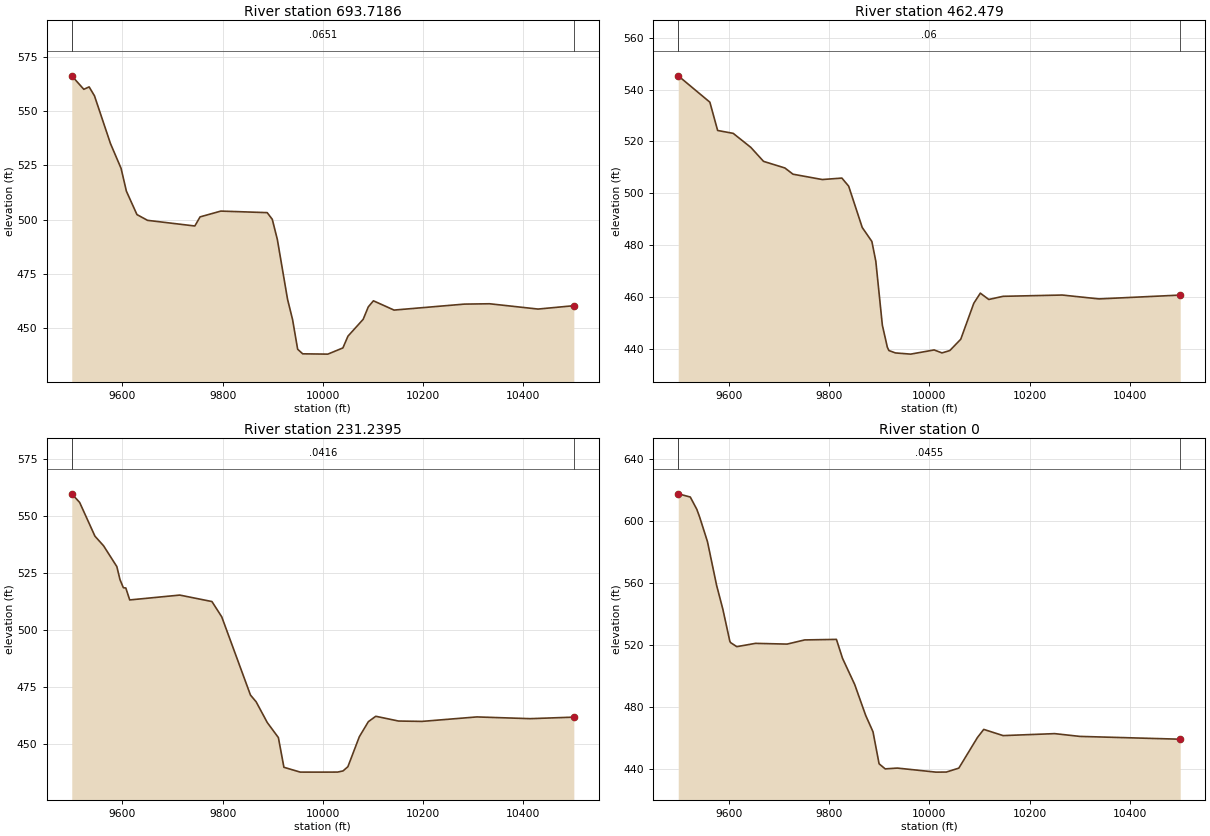
Type RM Length L Ch R = 1 ,693.7186,231.239600,231.239600,231.239600
XS GIS Cut Line= 6
 556312.43592106 814119.83511638556623.220113382814019.747294492
556733.060259017813997.687235834556867.397921507813984.842557319
556947.284607342  813966.0802895557271.491797975813845.307302773
#Sta/Elev= 30
9499.029 566.1639523.061559.96029533.711 561.0689544.362556.94439576.314 534.968
9597.456523.56219608.015 513.0889629.134502.30369650.252499.6596 9744.63497.0625
9755.067501.24719796.484503.91739888.996503.20959899.145500.14689909.293490.8517
9929.591463.37979939.723453.93249949.789440.35749959.855 438.23810010.02438.0978
 10040.1440.948310050.19446.365110080.55454.114810090.76459.837610100.97462.6367
10142.16458.367210282.74461.116110332.86461.271810429.54458.833610500.97460.3867
#Mann= 3 , 0 , 0
9499.029  0.0651       09499.029  0.0651       010500.97  0.0651       0
#XS Ineff= 2 , 0
       0                               0
Bank Sta=9499.029,10500.97
Exp/Cntr=0.3,0.1

Type RM Length L Ch R = 1 , 462.479,231.239500,231.239500,231.239500
XS GIS Cut Line= 6
556564.359788662814525.654458857556671.807507575814435.147363487
556778.222411047814333.909880146557043.230291196 814033.60152347
557158.254207209813947.788771344557307.318159563813866.025601205
#Sta/Elev= 30
9499.045545.34659562.149535.17489577.672524.25269608.716523.14489643.874517.7323
9669.254512.33349711.883509.77629728.061507.37549786.433505.31749825.592505.8791
9839.138502.75889866.228486.80479885.434481.41539893.302473.76529906.342449.1137
9916.219440.66089919.381439.31939932.421438.39369962.964437.931210009.68439.5456
10025.29438.403410040.91439.302410062.76443.670910088.81457.558510101.83461.4631
10118.76459.024910147.13460.241410265.27460.737910338.66459.243610500.89460.7209
#Mann= 3 , 0 , 0
9499.045    0.06       09499.045    0.06       010500.89    0.06       0
#XS Ineff= 2 , 0
       0                               0
Bank Sta=9499.045,10500.89
Exp/Cntr=0.3,0.1

Type RM Length L Ch R = 1 ,231.2395,231.239500,231.239500,231.239500
XS GIS Cut Line= 6
556854.654934719814702.851544968557036.804793613814462.855888885
557161.142007099814184.563791969557222.488468639814081.388166646
557315.753921475 813980.63822502557426.487308692813900.040075121
#Sta/Elev= 30
9499.055559.66539514.816555.88359545.288541.1326 9562.48536.92489588.989527.8017
9595.284522.08969601.972518.56879606.886518.43439614.708513.20469714.564  515.33
9778.751 512.4969798.294505.81769855.644471.55779866.926468.61149889.129459.5391
9911.332452.93259922.381439.92949954.858 437.821 9997.67437.811710029.67437.8352
10040.34438.339610050.03440.186210072.87453.321510090.79459.886210105.62462.2659
   10151 460.18310197.92460.021810307.37461.981710413.73461.219610500.88 461.891
#Mann= 3 , 0 , 0
9499.055  0.0416       09499.055  0.0416       010500.88  0.0416       0
#XS Ineff= 2 , 0
       0                               0
Bank Sta=9499.055,10500.88
Exp/Cntr=0.3,0.1

Type RM Length L Ch R = 1 ,       0,0.000000,0.000000,0.000000
XS GIS Cut Line= 6
557027.161768741814783.285001264557157.900269418814623.996555879
557342.493653346 814361.37690574557451.331804107814218.458057144
 557559.82752599814103.692809945557666.400204579814017.574878946
#Sta/Elev= 30
9499.024617.43169523.056 615.3769536.199607.37159541.924602.26769557.334586.5972
9575.628558.33419588.155542.81669601.914522.37879603.566521.38719615.904518.7799
9653.137520.90879716.251520.43679751.347523.12819814.721 523.477 9826.88511.2397
9851.199494.34449873.041474.45699887.677463.85179899.836443.18379911.996439.8931
9936.314440.407210013.32437.796410034.09437.846310058.96440.380910096.25460.2109
10108.68465.380510147.33461.3733 10250.3462.641110300.49460.857510500.94459.0443
#Mann= 3 , 0 , 0
9499.024  0.0455       09499.024  0.0455       010500.94  0.0455       0
#XS Ineff= 2 , 0
       0                               0
Bank Sta=9499.024,10500.94
Exp/Cntr=0.3,0.1